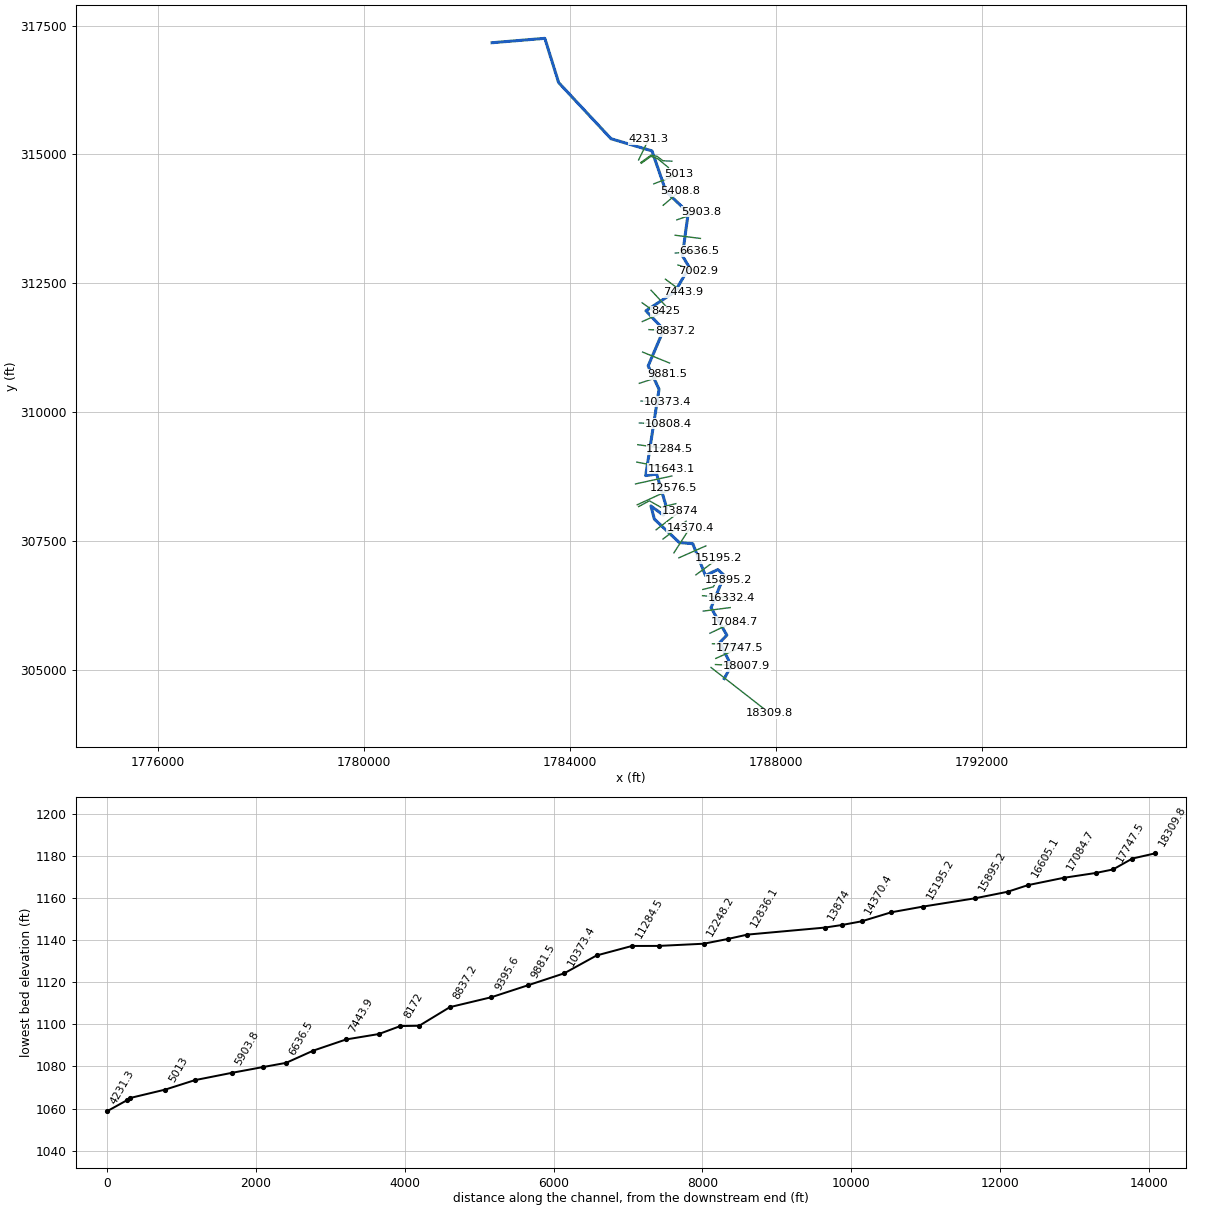
--- PlummerRun.prj (project) ---

Proj Title=PlummerRun
Current Plan=p01
Default Exp/Contr=0,0
English Units
Geom File=g01
Flow File=f01
Plan File=p01
BEGIN DESCRIPTION:
END DESCRIPTION:
DSS Export Rating Curves= 0
DSS Export Rating Curve Sorted= 0
DSS Export Volume Flow Curves= 0
DXF OffsetX= 0
DXF OffsetY= 0
DXF ScaleX= 0
DXF ScaleY= 0

--- PlummerRun.p01 (plan) ---

Plan Title=Floodplain
Program Version=4.00
Geom File=g01
Flow File=f01
K Sum by GR=0
Std Step Tol=0.01
Critical Tol=0.01
Num of Std Step Trials=20
Max Error Tol=0.3
Flow Tol Ratio=0.001
Split Flow NTrial=30
Split Flow Tol=0.02
Split Flow Ratio=0.02
Log Output Level=0
Friction Slope Method=1
Unsteady Friction Slope Method=2
Unsteady Bridges Friction Slope Method=1
Global Log Level=0
CheckData=False
Run HTab=0
Run UNet=0
Run PostProcess=0
UNET Theta=0
UNET Theta Warmup=0
UNET ZTol=0
UNET ZSATol=0
UNET MxIter=0
UNET MaxInSteps=0
UNET DtIC=0
UNET DtMin=0
UNET MaxCRTS=0
UNET WFStab=0
UNET SFStab=0
UNET WFX=0
UNET SFX=0
UNET DSS MLevel=0
UNET DZMax Abort=0
UNET Convert EG Bridges=0
UNET Use Existing IB Tables=0
UNET Froude Limit=0
UNET Froude Power=0
Write IC File=0
Echo Input=False
Echo Output=False
Write Detailed=0

--- PlummerRun.f01 (steady flow) ---

Flow Title=NFF Regression Equation
Program Version=4.10
Number of Profiles= 1
Profile Names=P100yr
River Rch & RM=PlummerRun,Main            ,18309.8
     956
River Rch & RM=PlummerRun,Main            ,15895.2
    1014
River Rch & RM=PlummerRun,Main            ,11284.5
    1124
River Rch & RM=PlummerRun,Main            ,6636.5
    1244
River Rch & RM=PlummerRun,Main            ,6320.7
    1539
River Rch & RM=PlummerRun,Main            ,4539.4
    1685
River Rch & RM=PlummerRun,Main            ,214.1
    1809
Boundary for River Rch & Prof#=PlummerRun,Main            , 1
Up Type= 0
Dn Type= 3
Dn Slope=0.011715
DSS Import GetInterval= 0
DSS Import GetPeak= 0
DSS Import FillOption= 0

--- PlummerRun.g01 (geometry) ---

Geom Title=USGS 10m DEM
Program Version=4.10

River Reach=PlummerRun      ,Main
Reach XY= 30
     1786999.284      304825.877     1787133.718      305077.556
     1786913.285      305528.103     1787049.354       305668.26
     1786742.119      306201.375     1786999.172      306827.573
     1786872.559      306942.575     1786634.106      306825.254
     1786386.968      307444.464     1786127.471      307465.608
     1785641.798      307921.798     1785574.691       308176.65
      1785817.09      307997.153     1785880.161      308140.162
     1785686.358      308795.836     1785473.203      308766.348
     1785732.856       310442.41     1785521.559       310895.77
     1785823.324      311599.381     1785478.574      311965.515
     1786040.526      312335.663     1786319.405      312812.127
     1786185.874      313033.192     1786299.543      313870.621
     1785867.976      314282.066     1785595.368      315069.365
      1784801.22      315305.457     1783783.199      316396.407
     1783515.403      317254.763      1782491.62       317169.59

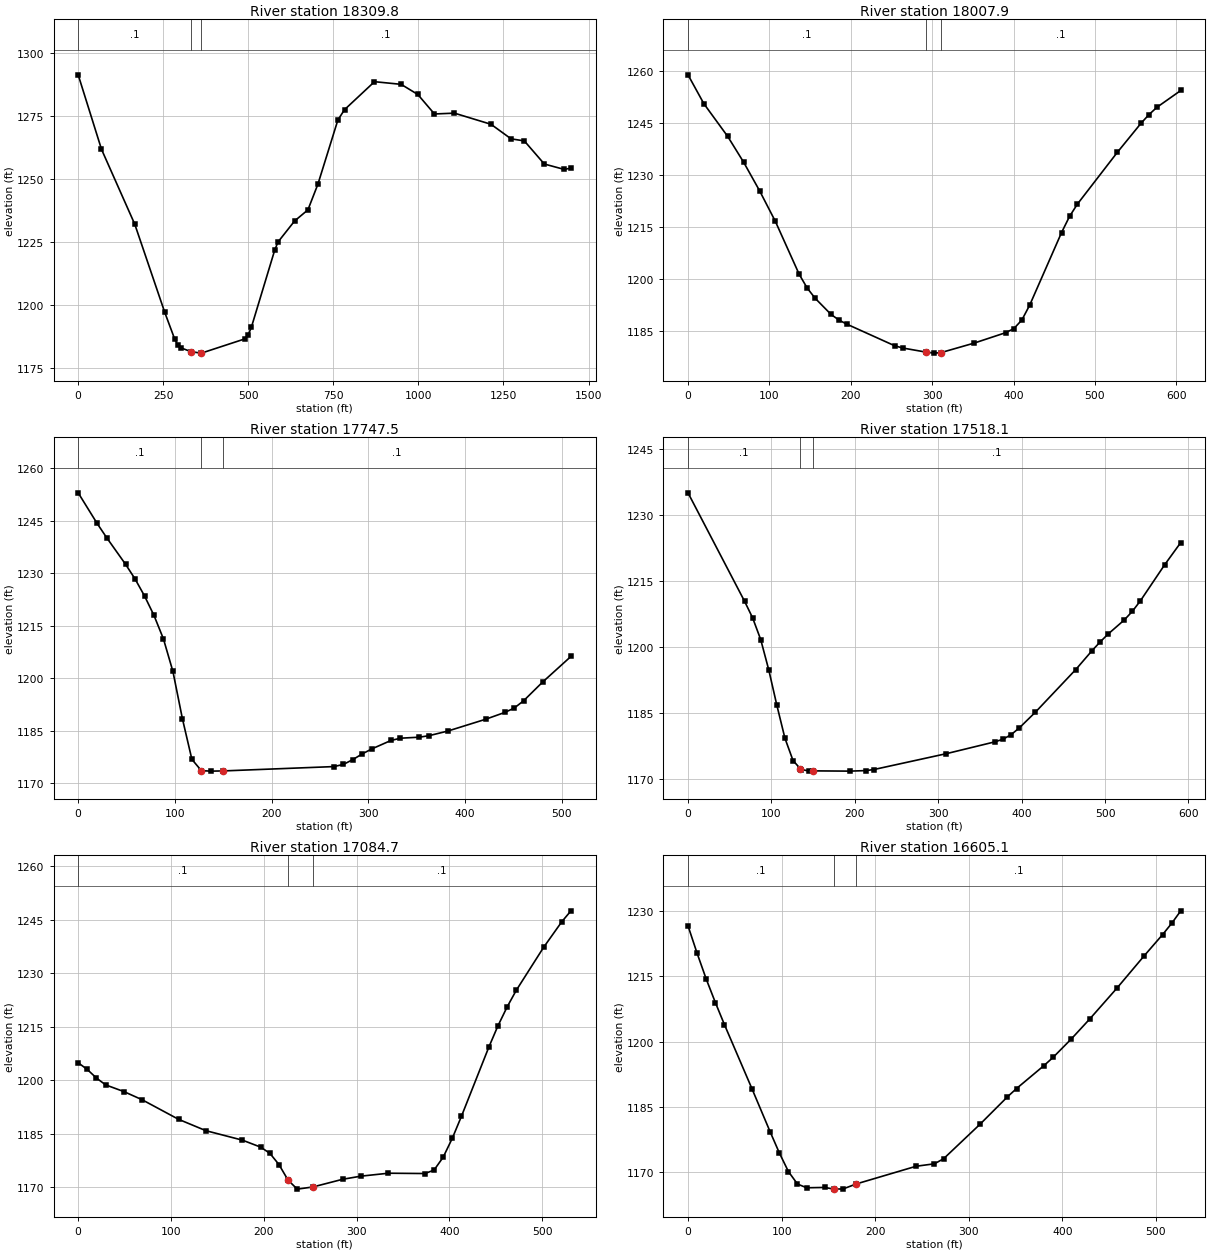
Type RM Length L Ch R = 1 ,18309.8 ,288.4,302,314.7
XS GIS Cut Line= 2
     1786742.006      305040.732      1787884.09      304150.109
#Sta/Elev= 30
       0 1291.39    68.5 1261.88   166.4 1232.14   254.4 1197.24   283.8 1186.58
   293.6 1184.14   303.4 1183.09   332.4 1181.61   362.1 1181.07   489.3 1186.69
   499.1 1188.13   508.9 1191.26   577.4  1221.8   587.2 1225.11   636.1 1233.46
   675.2 1237.86   704.6 1248.05   763.3  1273.5   782.9 1277.59   870.9 1288.67
   949.2 1287.62   998.2  1283.6  1047.1 1275.87  1105.8  1276.2  1213.4 1271.78
  1272.2 1266.02  1311.3 1265.19    1370 1256.03  1428.7 1253.89  1448.3 1254.43
#Mann= 3 , 0 , 0
       0      .1       0   332.4    .045       0   362.1      .1       0
Bank Sta=332.4,362.1
XS Rating Curve= 0 ,0
Exp/Cntr=0.3,0.1

Type RM Length L Ch R = 1 ,18007.9 ,248.9,260.4,271.4
XS GIS Cut Line= 2
     1786828.452      305098.399     1787433.173      305068.045
#Sta/Elev= 30
       0  1258.8    19.5 1250.48    48.8 1241.05    68.4 1233.61    87.9 1225.43
   107.4 1216.56   136.7  1201.3   146.5 1197.36   156.2 1194.44   175.8 1189.77
   185.6 1188.14   195.3 1186.96   253.9 1180.76   263.7 1180.11     293  1178.9
   302.7 1178.63   311.3 1178.81   351.6 1181.52   390.6 1184.54   400.4  1185.7
   410.2 1188.16   419.9 1192.48     459 1213.36   468.8 1218.01   478.5 1221.57
   527.4 1236.43   556.6 1244.83   566.4 1247.34   576.2 1249.45   605.5 1254.29
#Mann= 3 , 0 , 0
       0      .1       0     293    .045       0   311.3      .1       0
Bank Sta=293,311.3
XS Rating Curve= 0 ,0
Exp/Cntr=0.3,0.1

Type RM Length L Ch R = 1 ,17747.5 ,239.9,229.4,218.6
XS GIS Cut Line= 2
     1786833.964      305216.902     1787299.315      305424.828
#Sta/Elev= 30
       0    1253    19.6 1244.25    29.4 1240.21      49 1232.58    58.8  1228.4
    68.6 1223.54    78.4 1217.97    88.2 1211.24      98 1201.94   107.8 1188.45
   117.6 1176.83   127.4  1173.6   137.2 1173.46   150.2 1173.52   264.6 1174.76
   274.4 1175.38   284.2 1176.78     294 1178.41   303.8 1179.82   323.5 1182.22
   333.3 1182.87   352.9 1183.16   362.7 1183.58   382.3 1184.91   421.5 1188.29
   441.1 1190.22   450.9 1191.46   460.7 1193.56   480.3 1198.89   509.7 1206.24
#Mann= 3 , 0 , 0
       0      .1       0   127.4    .045       0   150.2      .1       0
Bank Sta=127.4,150.2
XS Rating Curve= 0 ,0
Exp/Cntr=0.3,0.1

Type RM Length L Ch R = 1 ,17518.1 ,421.4,433.4,445.4
XS GIS Cut Line= 2
     1786769.586      305502.107     1787359.659      305472.487
#Sta/Elev= 30
       0 1234.97    67.8 1210.36    77.5 1206.58    87.2 1201.64    96.8  1194.8
   106.5 1186.77   116.2 1179.28   125.9 1174.21   134.7 1172.34   135.6 1172.15
   145.3 1171.84   149.7 1171.86   193.7  1171.8   213.1 1171.92   222.8 1172.16
   309.9 1175.77     368 1178.45   377.7 1179.04   387.4 1180.08   397.1 1181.59
   416.5 1185.18   464.9 1194.86   484.3 1199.12     494  1201.1   503.6  1202.9
     523  1206.1   532.7 1208.06   542.4 1210.46   571.4 1218.62   590.8 1223.69
#Mann= 3 , 0 , 0
       0      .1       0   134.7    .045       0   149.7      .1       0
Bank Sta=134.7,149.7
XS Rating Curve= 0 ,0
Exp/Cntr=0.3,0.1

Type RM Length L Ch R = 1 ,17084.7 ,486.7,479.6,468.5
XS GIS Cut Line= 2
     1786719.414      305705.436     1787198.898      305933.335
#Sta/Elev= 30
       0 1204.91     9.8 1203.02    19.7 1200.62    29.5 1198.71    49.2 1196.83
    68.8 1194.55   108.1 1189.06   137.6 1185.87     177 1183.21   196.6 1181.26
   206.5 1179.53   216.3 1176.38   226.1 1172.02     236 1169.49   252.8 1170.09
   285.1 1172.26   304.8 1173.13   334.3 1173.95   373.6 1173.86   383.4 1174.83
   393.2 1178.42   403.1 1183.76   412.9 1189.89   442.4 1209.27   452.2 1215.23
   462.1 1220.53   471.9 1225.17   501.4 1237.23   521.1 1244.45   530.9 1247.48
#Mann= 3 , 0 , 0
       0      .1       0   226.1    .045       0   252.8      .1       0
Bank Sta=226.1,252.8
XS Rating Curve= 0 ,0
Exp/Cntr=0.3,0.1

Type RM Length L Ch R = 1 ,16605.1 ,276.5,272.7,271.1
XS GIS Cut Line= 2
     1786591.116      306135.604     1787113.322      306203.783
#Sta/Elev= 30
       0 1226.67     9.8  1220.3    19.5 1214.39    29.3 1208.97      39 1203.88
    68.3 1189.18    87.8 1179.22    97.5 1174.42   107.3 1170.08     117  1167.2
   126.8 1166.34   146.3 1166.42     156 1166.03   165.8 1166.08   179.9 1167.23
   243.8  1171.3   263.3 1171.86   273.1 1173.02   312.1 1180.98   341.3 1187.27
   351.1  1189.2   380.4 1194.48   390.1 1196.36   409.6 1200.61   429.1 1205.16
   458.4 1212.32   487.6 1219.79   507.1 1224.63   516.9 1227.24   526.6 1230.12
#Mann= 3 , 0 , 0
       0      .1       0     156    .045       0   179.9      .1       0
Bank Sta=156,179.9
XS Rating Curve= 0 ,0
Exp/Cntr=0.3,0.1

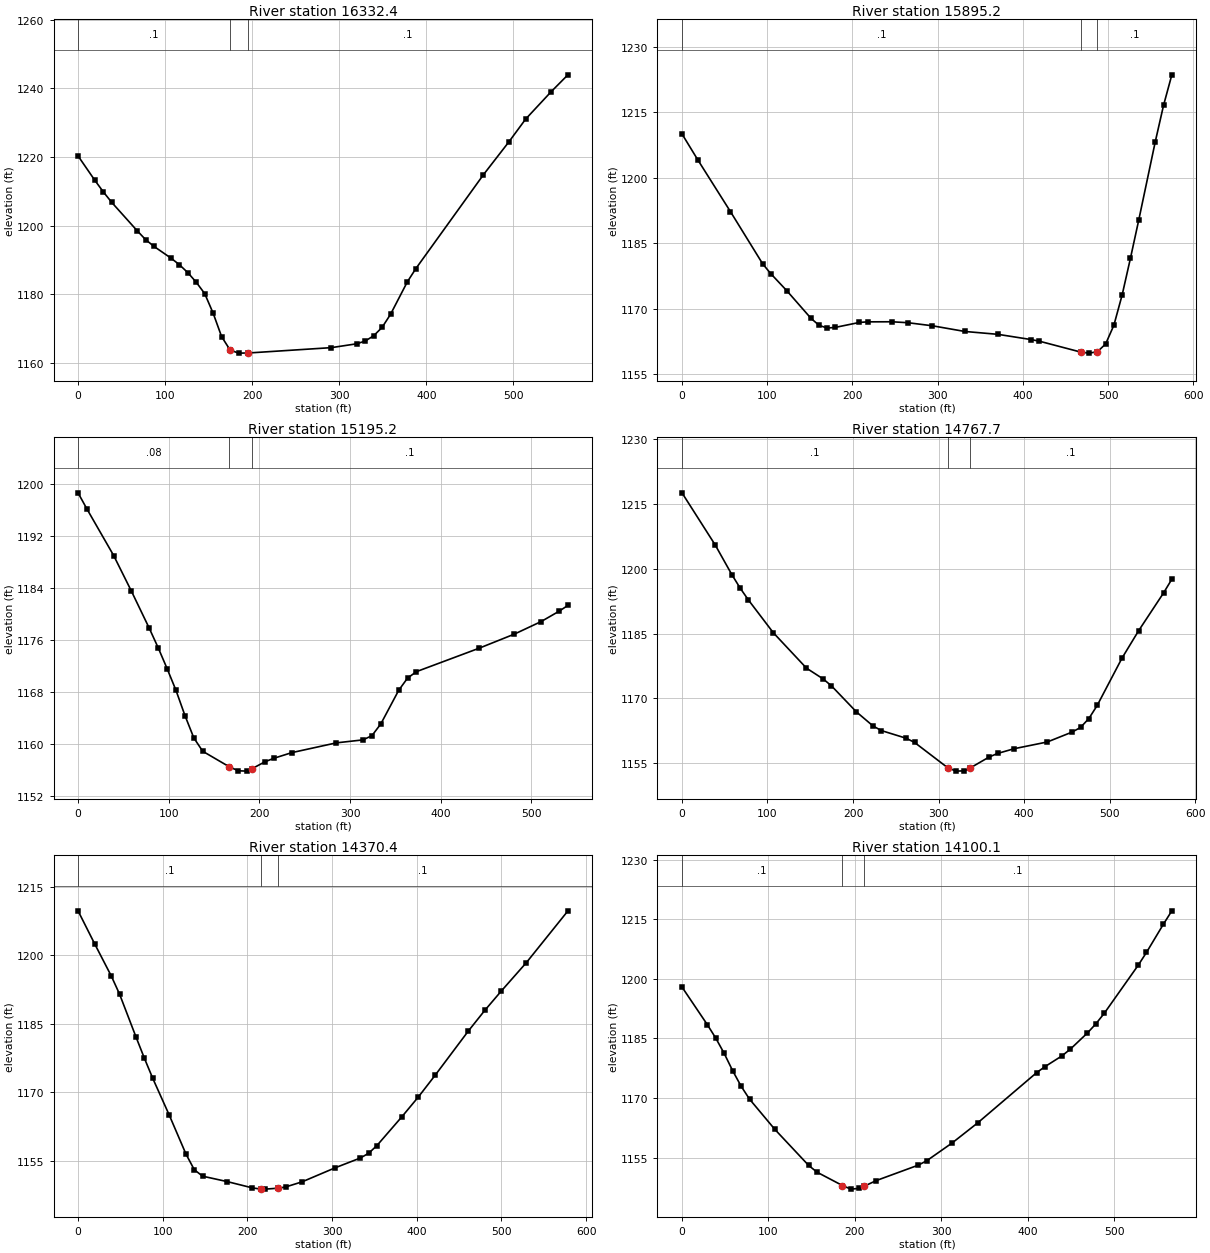
Type RM Length L Ch R = 1 ,16332.4 ,429.7,437.1,443.6
XS GIS Cut Line= 2
     1786576.528      306435.048     1787136.776        306383.6
#Sta/Elev= 30
       0  1220.3    19.4 1213.16    29.1 1209.81    38.8 1206.74    67.9 1198.52
    77.6 1195.93    87.3 1193.94   106.7 1190.55   116.4 1188.63   126.1 1186.31
   135.8 1183.51   145.5  1180.2   155.2 1174.49   164.9 1167.68   174.6  1163.8
   184.3 1162.88   195.6 1162.92     291 1164.48   320.1  1165.6   329.8  1166.4
   339.5 1167.93   349.2 1170.37   358.9 1174.18   378.3 1183.68     388  1187.5
   465.6 1214.83   494.7 1224.35   514.1 1231.03   543.2 1238.95   562.6 1243.91
#Mann= 3 , 0 , 0
       0      .1       0   174.6    .045       0   195.6      .1       0
Bank Sta=174.6,195.6
XS Rating Curve= 0 ,0
Exp/Cntr=0.3,0.1

Type RM Length L Ch R = 1 ,15895.2 ,689.2,700,709.9
XS GIS Cut Line= 4
      1786583.63      306555.784     1786785.824      306605.771
     1786845.734      306713.845     1787086.226      306748.624
#Sta/Elev= 30
       0 1210.05    18.9    1204    56.8 1192.26    94.7 1180.26   104.1 1178.03
   123.1 1174.08   151.5 1167.74   160.9 1166.16   170.4 1165.54   179.9 1165.69
   208.3 1166.83   217.8 1166.96   246.3 1166.98   265.3 1166.76   293.8 1166.06
   331.8 1164.76   370.7  1164.1   409.6  1162.9   419.3 1162.53   467.9 1160.03
   477.6 1159.79   487.4  1160.1   497.1 1161.89   506.8 1166.19   516.5 1173.14
   526.2 1181.52     536 1190.33   555.4  1208.3   565.1 1216.63   574.8  1223.6
#Mann= 3 , 0 , 0
       0      .1       0   467.9    .045       0   487.4      .1       0
Bank Sta=467.9,487.4
XS Rating Curve= 0 ,0
Exp/Cntr=0.3,0.1

Type RM Length L Ch R = 1 ,15195.2 ,432.4,427.5,421.8
XS GIS Cut Line= 2
     1786448.512      306839.034     1786883.135      307159.821
#Sta/Elev= 30
       0 1198.59     9.8 1196.11    39.3 1188.96    58.9 1183.48    78.6 1177.78
    88.4 1174.79    98.2  1171.6     108 1168.26   117.9 1164.39   127.7 1160.95
   137.5  1158.9     167  1156.5   176.8  1155.9   186.6 1155.85   191.4 1156.19
   206.2 1157.29   216.1 1157.83   235.7 1158.69   284.8 1160.19   314.3 1160.65
   324.1  1161.3   333.9  1163.1   353.6 1168.26   363.4 1170.14   373.2 1171.13
     442 1174.71   481.3  1176.9   510.7 1178.82   530.4  1180.4   540.2  1181.3
#Mann= 3 , 0 , 0
       0     .08       0     167    .045       0   191.4      .1       0
Bank Sta=167,191.4
XS Rating Curve= 0 ,0
Exp/Cntr=0.3,0.1

Type RM Length L Ch R = 1 ,14767.7 ,384.3,397.3,409.2
XS GIS Cut Line= 2
     1786117.597      307169.948     1786641.641      307401.316
#Sta/Elev= 30
       0 1217.57    38.8 1205.52    58.3 1198.64      68 1195.52    77.7 1192.76
   106.8 1185.18   145.6 1176.98   165.1 1174.48   174.8 1172.88   203.9 1166.87
   223.3 1163.61     233 1162.54   262.2 1160.75   271.9 1159.79   310.7 1153.93
   320.4 1153.14   330.1 1153.21   337.1 1153.88   359.2 1156.41     369 1157.23
   388.4 1158.33   427.2 1159.89   456.3 1162.19     466 1163.25   475.8 1165.32
   485.5 1168.34   514.6 1179.33     534 1185.66   563.1 1194.39   572.8 1197.57
#Mann= 3 , 0 , 0
       0      .1       0   310.7    .045       0   337.1      .1       0
Bank Sta=310.7,337.1
XS Rating Curve= 0 ,0
Exp/Cntr=0.3,0.1

Type RM Length L Ch R = 1 ,14370.4 ,278.1,270.3,263.4
XS GIS Cut Line= 2
     1786021.298      307266.248     1786333.956      307752.963
#Sta/Elev= 30
       0 1209.69    19.6 1202.49    39.2 1195.47      49  1191.5    68.6 1182.05
    78.4 1177.45    88.2 1173.09   107.8 1165.01   127.5 1156.51   137.3  1153.1
   147.1 1151.69   176.5 1150.49   205.9 1149.13   215.7 1148.87     221 1148.86
     236 1149.06   245.1 1149.33   264.7 1150.46     304 1153.55   333.4 1155.66
   343.2  1156.7     353 1158.39   382.4 1164.67     402 1169.03   421.6 1173.72
   460.8 1183.39   480.4 1187.94     500 1192.19   529.5 1198.38   578.5 1209.67
#Mann= 3 , 0 , 0
       0      .1       0   215.7    .045       0     236      .1       0
Bank Sta=215.7,236
XS Rating Curve= 0 ,0
Exp/Cntr=0.3,0.1

Type RM Length L Ch R = 1 ,14100.1 ,226.1,226.1,226
XS GIS Cut Line= 2
     1785810.375      307535.049     1786258.998      307880.833
#Sta/Elev= 30
       0 1197.94    29.3 1188.48    39.1 1185.07    48.8 1181.24    58.6 1176.88
    68.4 1172.97    78.1 1169.73   107.4 1162.11   146.5 1153.04   156.2 1151.34
   185.6 1147.98   195.3 1147.08   205.1 1147.27   210.4 1147.78   224.6 1149.23
   273.4 1153.13   283.2 1154.25   312.5 1158.72   341.8 1163.73   410.2 1176.42
   419.9 1177.93   439.5 1180.64   449.2 1182.34   468.8 1186.38   478.5 1188.66
   488.3 1191.34   527.4 1203.39   537.1 1206.66   556.6 1213.74   566.4 1217.12
#Mann= 3 , 0 , 0
       0      .1       0   185.6    .045       0   210.4      .1       0
Bank Sta=185.6,210.4
XS Rating Curve= 0 ,0
Exp/Cntr=0.3,0.1

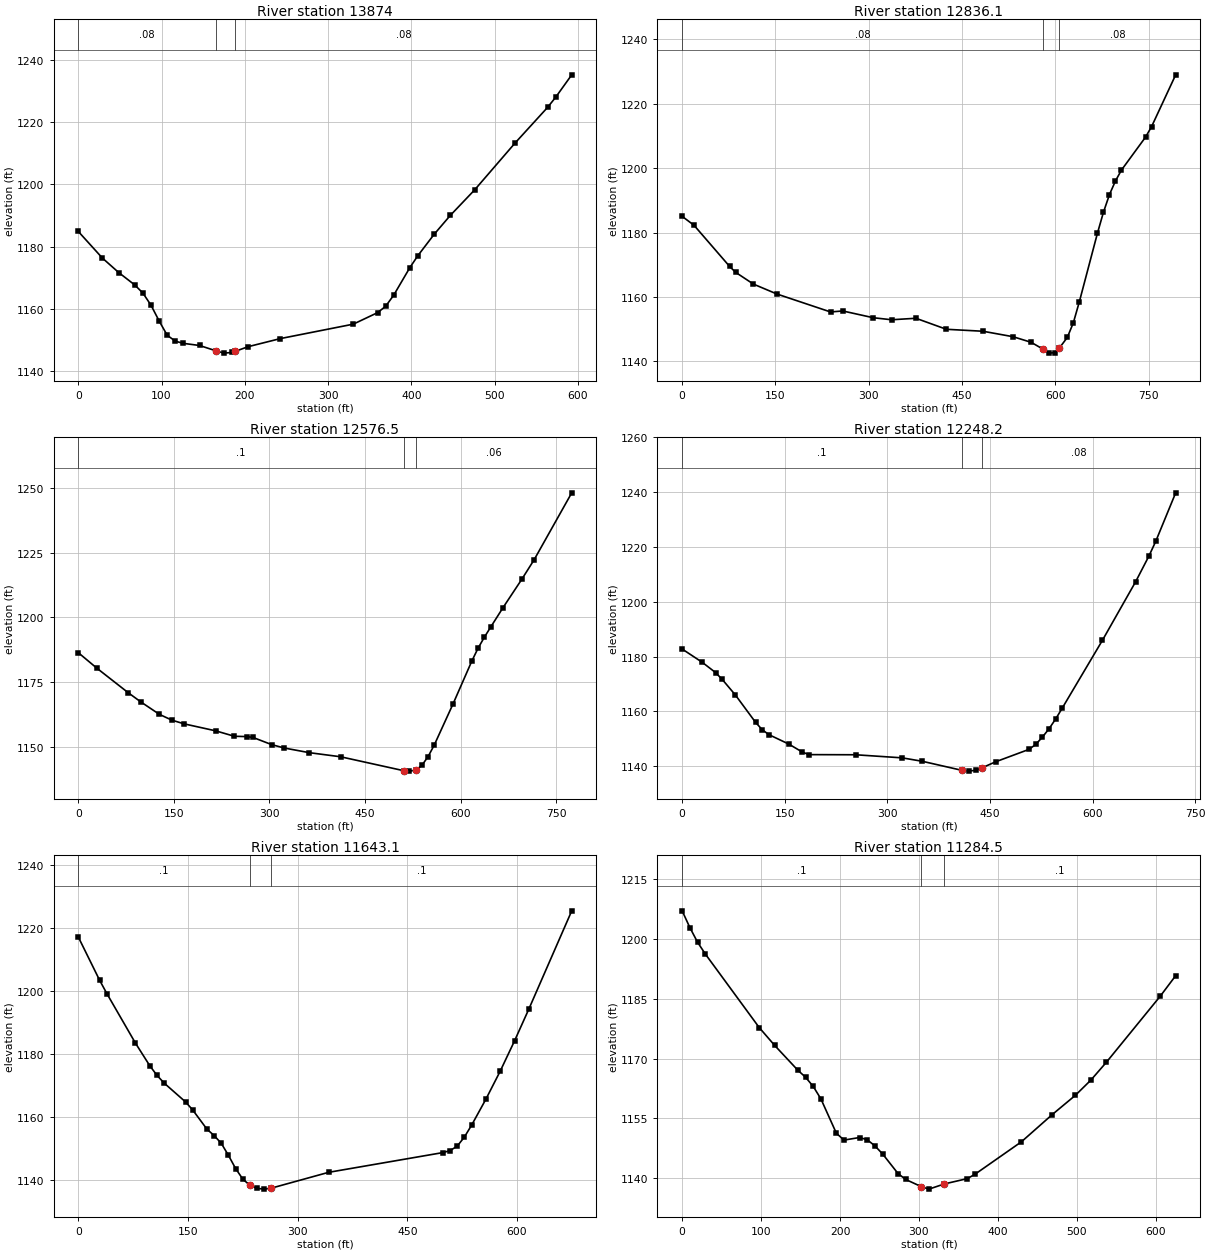
Type RM Length L Ch R = 1 ,13874   ,1046.1,1038,1027.4
XS GIS Cut Line= 2
     1785675.633      307713.772     1786144.902      308075.468
#Sta/Elev= 30
       0 1184.93    29.1 1176.35    48.6 1171.73      68 1167.72    77.7 1165.13
    87.4 1161.24    97.1 1156.22   106.8 1151.62   116.6 1149.71   126.3 1149.01
   145.7 1148.33   165.1 1146.64   174.8 1145.88   184.5 1146.09   188.8 1146.48
     204 1147.95   242.8 1150.55   330.2 1155.17   359.4 1158.86   369.1 1160.91
   378.8 1164.48   398.2 1173.33   407.9 1177.19   427.4 1184.02   446.8 1190.08
   475.9 1198.23   524.5 1213.28   563.4 1224.67   573.1 1227.91   592.5 1235.14
#Mann= 3 , 0 , 0
       0     .08       0   165.1    .045       0   188.8     .08       0
Bank Sta=165.1,188.8
XS Rating Curve= 0 ,0
Exp/Cntr=0.3,0.1

Type RM Length L Ch R = 1 ,12836.1 ,255.5,259.6,263.6
XS GIS Cut Line= 4
      1785335.93      308164.357     1785546.305      308276.718
     1785767.805      308150.821     1786059.216      308221.637
#Sta/Elev= 30
       0 1185.02    19.1 1182.24    76.3 1169.47    85.9 1167.65   114.5 1163.99
   152.6 1160.89   238.5 1155.34   258.1 1155.65   307.1 1153.55   336.5 1152.92
   375.7 1153.38   424.7 1149.96   483.5 1149.35     532 1147.65     561 1145.91
   580.4 1143.75     590 1142.56   599.7 1142.74   605.7    1144     619 1147.42
   628.7 1151.96   638.4 1158.52   667.4 1179.74   677.1 1186.29   686.8 1191.79
   696.4    1196   706.1  1199.4   744.8 1209.62   754.5 1212.88   793.2 1228.95
#Mann= 3 , 0 , 0
       0     .08       0   580.4    .045       0   605.7     .08       0
Bank Sta=580.4,605.7
XS Rating Curve= 0 ,0
Exp/Cntr=0.3,0.1

Type RM Length L Ch R = 1 ,12576.5 ,332.9,328.3,323.6
XS GIS Cut Line= 2
     1785309.058      308200.001     1786012.971      308522.241
#Sta/Elev= 30
       0  1186.4    29.4 1180.34    78.4 1170.88      98 1167.35   127.4 1162.49
     147 1160.25   166.6 1158.79   215.6 1156.12     245 1154.01   264.6 1153.89
   274.4 1153.54   303.8 1150.75   323.4 1149.46   362.6 1147.66   411.6 1146.08
   511.1 1140.66   519.4 1140.52   529.2 1140.87     539 1142.71   548.8 1146.12
   558.6 1150.66     588 1166.54   617.4  1183.1   627.2 1188.08     637 1192.31
   646.8 1196.18   666.4 1203.81   695.8 1214.76   715.4 1222.43   774.2 1248.25
#Mann= 3 , 0 , 0
       0      .1       0   511.1    .045       0   529.2     .06       0
Bank Sta=511.1,529.2
XS Rating Curve= 0 ,0
Exp/Cntr=0.3,0.1

Type RM Length L Ch R = 1 ,12248.2 ,615.2,605.1,577.5
XS GIS Cut Line= 2
     1785275.974      308604.632     1785981.069      308758.316
#Sta/Elev= 30
       0 1182.77    29.3 1177.94    48.8 1174.19    58.5 1171.71      78 1165.95
   107.3 1156.04     117 1153.36   126.8 1151.54     156 1148.09   175.5 1145.21
   185.3 1144.25   253.6  1144.2   321.8 1143.07   351.1 1141.82   409.6 1138.49
   419.3 1138.23   429.1 1138.55   438.8 1139.47   458.3 1141.63   507.1 1146.16
   516.9 1147.95   526.6  1150.6   536.4 1153.67   546.1 1157.24   555.9 1161.28
   614.4 1185.91   663.1 1207.34   682.6 1216.75   692.4 1222.02   721.6 1239.75
#Mann= 3 , 0 , 0
       0      .1       0   409.6    .045       0   438.8     .08       0
Bank Sta=409.6,438.8
XS Rating Curve= 0 ,0
Exp/Cntr=0.3,0.1

Type RM Length L Ch R = 1 ,11643.1 ,357.4,358.6,359.6
XS GIS Cut Line= 2
     1785300.783       309027.94     1785963.558      308901.182
#Sta/Elev= 30
       0 1217.29    29.3 1203.49    39.1  1199.3    78.2 1183.57    97.8 1176.39
   107.6 1173.34   117.4 1170.88   146.7 1164.89   156.5 1162.34     176 1156.23
   185.8  1154.2   195.6 1151.74   205.4 1147.91   215.2 1143.73   224.9 1140.42
   234.7 1138.39   244.5 1137.43   254.3 1137.19     264  1137.5   342.3 1142.52
   498.8  1148.8   508.5 1149.42   518.3 1150.86   528.1 1153.76   537.9  1157.5
   557.4 1165.74     577 1174.65   596.6 1184.27   616.1 1194.34   674.8 1225.55
#Mann= 3 , 0 , 0
       0      .1       0   234.7    .045       0     264      .1       0
Bank Sta=234.7,264
XS Rating Curve= 0 ,0
Exp/Cntr=0.3,0.1

Type RM Length L Ch R = 1 ,11284.5 ,473.3,476,478.4
XS GIS Cut Line= 2
     1785320.587      309365.847     1785939.871      309280.175
#Sta/Elev= 30
       0 1207.12     9.8  1202.9    19.5 1199.24    29.3 1196.28    97.7 1177.76
   117.2 1173.29   146.5 1167.07   156.3  1165.3   166.1 1162.97   175.8 1159.84
   195.4  1151.2   205.1  1149.5   224.7 1150.14   234.4 1149.59   244.2 1148.04
     254    1146   273.5 1141.08   283.3 1139.59   302.8 1137.81   312.6 1137.17
   332.1 1138.47   361.4 1139.82   371.2 1140.94   429.8 1149.07   468.9 1155.92
   498.2 1160.76   517.7 1164.56   537.3 1169.03   605.6 1185.65   625.2 1190.82
#Mann= 3 , 0 , 0
       0      .1       0   302.8    .045       0   332.1      .1       0
Bank Sta=302.8,332.1
XS Rating Curve= 0 ,0
Exp/Cntr=0.3,0.1

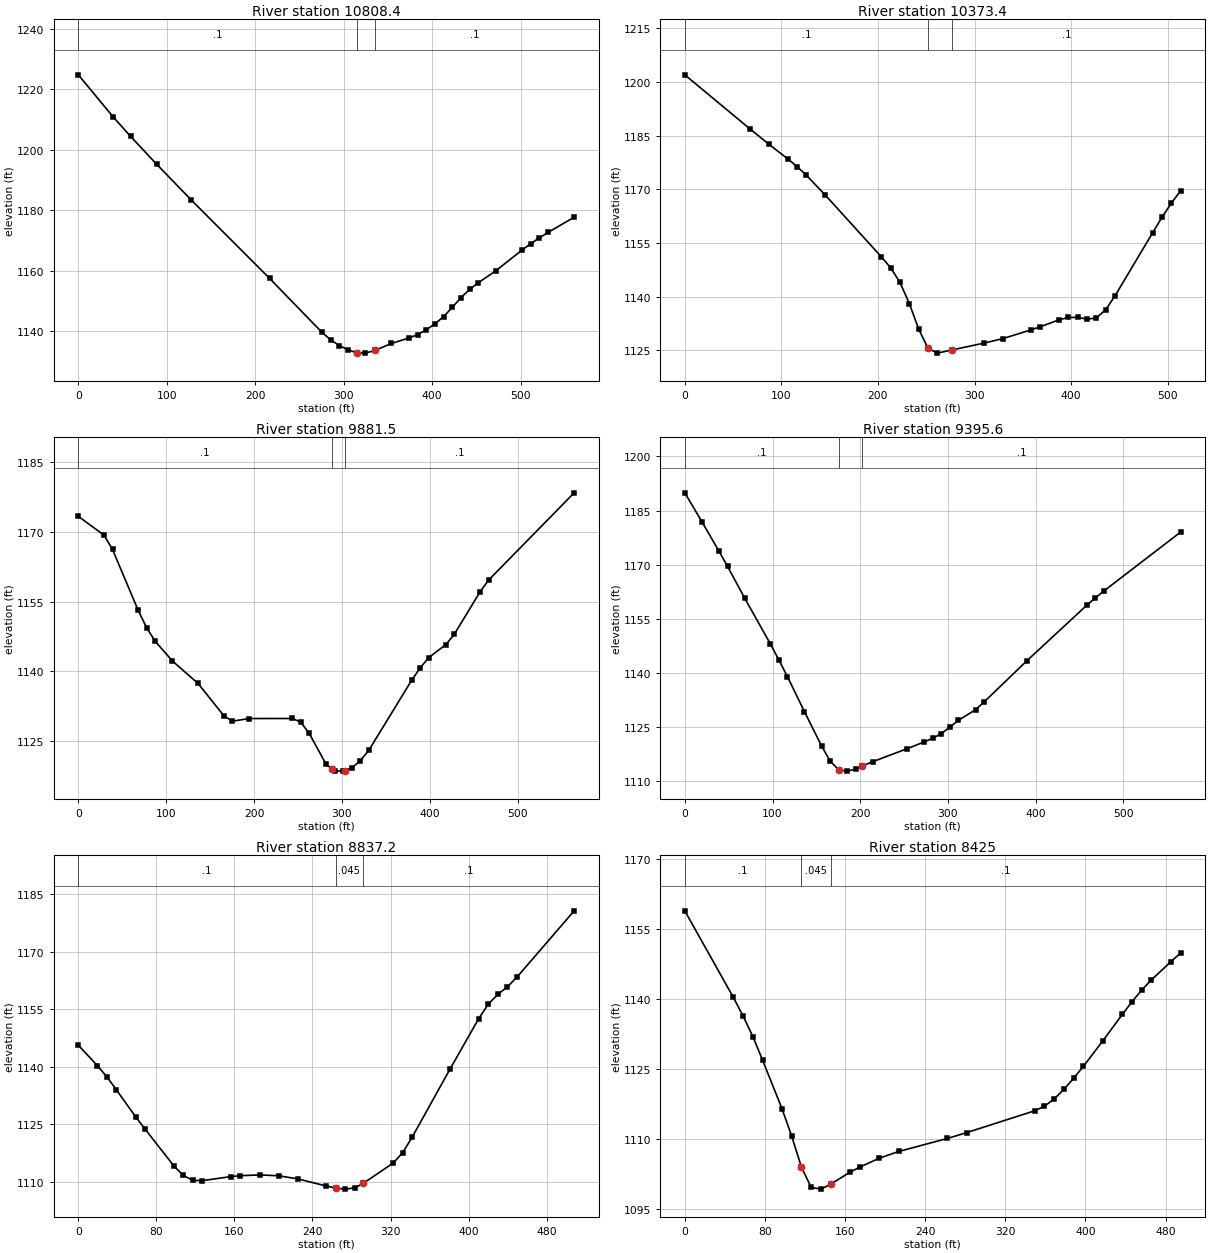
Type RM Length L Ch R = 1 ,10808.4 ,434.7,435,434.8
XS GIS Cut Line= 2
     1785350.749      309787.076     1785910.928      309769.386
#Sta/Elev= 29
       0 1224.79    39.3 1210.88      59 1204.43    88.5  1195.2   127.8 1183.31
   216.3 1157.37   275.3 1139.58   285.2 1137.06     295 1135.17   304.8 1133.76
   314.6 1132.79   324.5 1132.66     335 1133.53     354 1135.86   373.6 1137.67
   383.5 1138.79   393.3 1140.38   403.1 1142.36     413 1144.76   422.8 1147.83
   432.6 1151.06   442.5 1153.78   452.3 1155.99     472 1159.94   501.5 1166.76
   511.3 1168.86   521.1 1170.82     531 1172.63   560.5 1177.64
#Mann= 3 , 0 , 0
       0      .1       0   314.6    .045       0     335      .1       0
Bank Sta=314.6,335
XS Rating Curve= 0 ,0
Exp/Cntr=0.3,0.1

Type RM Length L Ch R = 1 ,10373.4 ,483.6,491.9,498.4
XS GIS Cut Line= 2
      1785382.75      310213.286     1785895.922      310197.081
#Sta/Elev= 30
       0 1202.03    67.8 1186.83    87.2 1182.59   106.6 1178.52   116.2 1176.38
   125.9 1173.94   145.3 1168.44   203.4 1151.16   213.1 1148.09   222.8 1143.96
   232.5 1138.05   242.2  1130.9   251.9 1125.49   261.6 1124.19   276.9  1125.1
     310    1127   329.4 1128.26   358.4 1130.68   368.1 1131.56   387.5  1133.5
   397.2 1134.18   406.9 1134.18   416.6  1133.7   426.2 1134.03   435.9 1136.36
   445.6 1140.27   484.4 1157.85     494 1162.13   503.7  1166.1   513.4 1169.62
#Mann= 3 , 0 , 0
       0      .1       0   251.9    .045       0   276.9      .1       0
Bank Sta=251.9,276.9
XS Rating Curve= 0 ,0
Exp/Cntr=0.3,0.1

Type RM Length L Ch R = 1 ,9881.5  ,501.3,485.9,470.3
XS GIS Cut Line= 2
     1785350.028      310557.399     1785886.181      310733.067
#Sta/Elev= 30
       0 1173.34    29.2 1169.29    38.9 1166.21    68.1  1153.1    77.8  1149.3
    87.6  1146.4     107  1142.2   136.2 1137.35   165.4 1130.44   175.1 1129.22
   194.6 1129.79   243.2  1129.8   252.9 1129.05   262.6 1126.62   282.1 1119.89
   288.3 1119.01   291.8 1118.52   301.6 1118.46   303.3 1118.59   311.3 1119.18
     321 1120.73   330.7 1122.99   379.4 1138.07   389.1 1140.72   398.8 1142.93
   418.3 1145.73     428 1147.98   457.2 1157.12   466.9 1159.62   564.2 1178.41
#Mann= 3 , 0 , 0
       0      .1       0   288.3    .045       0   303.3      .1       0
Bank Sta=288.3,303.3
XS Rating Curve= 0 ,0
Exp/Cntr=0.3,0.1

Type RM Length L Ch R = 1 ,9395.6  ,550.7,558.5,565.6
XS GIS Cut Line= 2
     1785413.553      311163.986     1785937.251      310951.278
#Sta/Elev= 29
       0 1189.91    19.5 1181.92      39 1173.73    48.7 1169.54    68.2 1160.78
    97.5  1148.1   107.2 1143.66     117 1139.01   136.4 1129.33   155.9 1119.83
   165.7 1115.64   175.4 1113.22   185.2 1112.86   194.9 1113.45   201.9 1114.26
   214.4 1115.49   253.4 1119.07   272.9 1120.94   282.6 1121.96   292.4 1123.25
   302.1 1125.02   311.9 1126.94   331.4 1129.85   341.1 1131.99   389.8 1143.38
     458 1158.74   467.8 1160.79   477.5 1162.69   565.2 1179.04
#Mann= 3 , 0 , 0
       0      .1       0   175.4    .045       0   201.9      .1       0
Bank Sta=175.4,201.9
XS Rating Curve= 0 ,0
Exp/Cntr=0.3,0.1

Type RM Length L Ch R = 1 ,8837.2  ,401.4,412.2,423
XS GIS Cut Line= 2
      1785536.65      311600.219     1786044.064      311572.639
#Sta/Elev= 30
       0 1145.63    19.5 1140.34    29.3 1137.38    39.1    1134    58.6 1127.03
    68.4 1123.79    97.7 1114.27   107.5 1111.72   117.3 1110.44     127 1110.35
   156.4 1111.42   166.1 1111.65   185.7 1111.85   205.2 1111.63   224.8 1110.83
   254.1 1108.96   263.8 1108.45   273.6 1108.15   283.4 1108.48   291.9 1109.64
   322.5  1114.9   332.3  1117.6     342 1121.61   381.1 1139.49   410.4 1152.58
   420.2 1156.36     430 1158.89   439.8 1160.86   449.5 1163.36   508.2 1180.65
#Mann= 3 , 0 , 0
       0      .1       0   263.8    .045       0   291.9      .1       0
Bank Sta=263.8,291.9
XS Rating Curve= 0 ,0
Exp/Cntr=0.3,0.1

Type RM Length L Ch R = 1 ,8425    ,276.8,253,229.1
XS GIS Cut Line= 2
     1785407.313      311756.013     1785858.805       311959.01
#Sta/Elev= 30
       0 1158.82    48.5  1140.3    58.2 1136.33      68 1131.91    77.6 1126.92
    97.1 1116.48   106.8 1110.58   116.5 1103.97   126.2 1099.69   135.9 1099.31
   145.6 1100.36     165 1102.94   174.7 1104.01   194.1 1105.92   213.5 1107.36
   262.1 1110.14   281.5  1111.4   349.4 1116.07   359.1 1117.05   368.8 1118.59
   378.6 1120.67   388.3 1123.04     398 1125.58   417.4 1131.04   436.8 1136.67
   446.5 1139.39   456.2 1141.89   465.9 1144.06   485.3 1147.95     495 1149.81
#Mann= 3 , 0 , 0
       0      .1       0   116.5    .045       0   145.6      .1       0
Bank Sta=116.5,145.6
XS Rating Curve= 0 ,0
Exp/Cntr=0.3,0.1

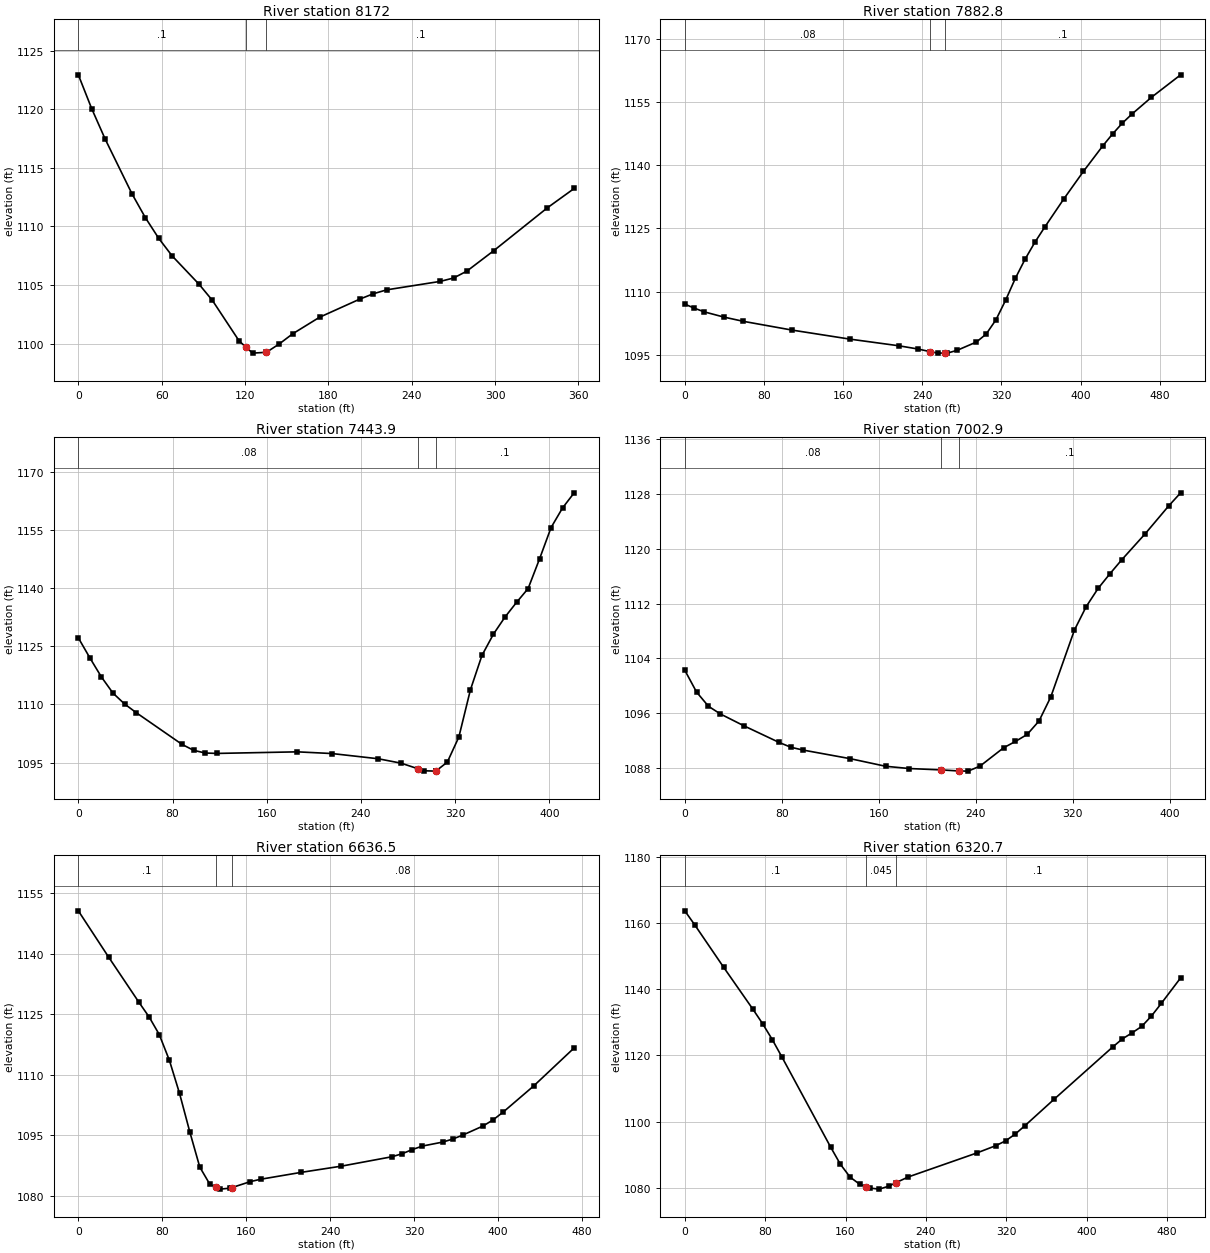
Type RM Length L Ch R = 1 ,8172    ,293.5,289.2,284.9
XS GIS Cut Line= 2
     1785404.578      312121.466     1785692.619      311910.729
#Sta/Elev= 25
       0 1122.93     9.6 1120.05    19.3 1117.45    38.6 1112.78    48.2 1110.75
    57.9 1108.97    67.5 1107.48    86.8 1105.07    96.5 1103.68   115.8 1100.21
   120.4 1099.72   125.4 1099.18   135.4 1099.25   144.7 1099.97   154.3 1100.83
   173.6 1102.24   202.6 1103.79   212.2 1104.24   221.9 1104.58   260.4  1105.3
   270.1 1105.59   279.7 1106.18     299 1107.92   337.6 1111.58   356.9 1113.23
#Mann= 3 , 0 , 0
       0      .1       0   120.4    .045       0   135.4      .1       0
Bank Sta=120.4,135.4
XS Rating Curve= 0 ,0
Exp/Cntr=0.3,0.1

Type RM Length L Ch R = 1 ,7882.8  ,434.5,438.9,443.2
XS GIS Cut Line= 2
     1785577.471      312364.797     1785919.004       311998.23
#Sta/Elev= 30
       0 1107.02     9.8 1106.05    19.6 1105.19    39.3 1103.96    58.9 1102.95
   108.1 1100.87     167 1098.71   216.1 1097.14   235.8 1096.36   247.9 1095.74
   255.4  1095.4   262.9 1095.39   265.2 1095.39   275.1 1096.05   294.7 1098.03
   304.5 1099.91   314.4  1103.3   324.2 1107.97     334 1113.15   343.8 1117.68
   353.7 1121.69   363.5 1125.24   383.1 1132.04   402.8 1138.54   422.4 1144.61
   432.2 1147.41   442.1 1149.99   451.9 1152.16   471.5 1156.12     501 1161.46
#Mann= 3 , 0 , 0
       0     .08       0   247.9    .045       0   262.9      .1       0
Bank Sta=247.9,262.9
XS Rating Curve= 0 ,0
Exp/Cntr=0.3,0.1

Type RM Length L Ch R = 1 ,7443.9  ,433.6,441,448.4
XS GIS Cut Line= 2
     1785856.018      312579.304     1786193.901      312328.107
#Sta/Elev= 30
       0 1127.17     9.8 1122.01    19.6 1117.09    29.4 1112.94    39.2 1110.15
      49 1107.93    88.1 1099.71    97.9 1098.19   107.7  1097.5   117.5 1097.39
     186  1097.8   215.4 1097.36   254.6 1096.02   274.2 1094.87   288.8  1093.4
   293.7 1092.92   303.5 1092.83   303.8  1092.9   313.3 1095.15   323.1 1101.62
   332.9 1113.77   342.7 1122.64   352.5 1128.15   362.3 1132.54   372.1 1136.32
   381.9 1139.87   391.7 1147.59   401.4  1155.6   411.2 1160.67     421 1164.54
#Mann= 3 , 0 , 0
       0     .08       0   288.8    .045       0   303.8      .1       0
Bank Sta=288.8,303.8
XS Rating Curve= 0 ,0
Exp/Cntr=0.3,0.1

Type RM Length L Ch R = 1 ,7002.9  ,357.3,366.3,375.3
XS GIS Cut Line= 2
     1786100.208      312854.335     1786489.594       312729.03
#Sta/Elev= 28
       0 1102.27     9.7 1099.08    19.5 1097.01    29.2  1095.9    48.7 1094.16
    77.9 1091.72    87.6 1091.02    97.4 1090.62   136.4 1089.36   165.6 1088.25
     185 1087.92   211.3 1087.72   226.3 1087.56   233.7 1087.54   243.5 1088.27
     263 1090.95   272.7 1091.87   282.4 1092.89   292.2 1094.86   301.9 1098.37
   321.4 1108.13   331.1 1111.55   340.9  1114.2   350.6 1116.33   360.4 1118.38
   379.8 1122.19   399.3 1126.28     409 1128.16
#Mann= 3 , 0 , 0
       0     .08       0   211.3    .045       0   226.3      .1       0
Bank Sta=211.3,226.3
XS Rating Curve= 0 ,0
Exp/Cntr=0.3,0.1

Type RM Length L Ch R = 1 ,6636.5  ,320.7,315.9,311.2
XS GIS Cut Line= 2
     1786047.616      313086.062     1786518.364      313126.052
#Sta/Elev= 30
       0  1150.6    28.9 1139.13    57.8 1127.94    67.5 1124.31    77.1 1119.98
    86.8 1113.57    96.4 1105.44   106.1 1095.98   115.7 1087.18   125.3 1082.92
   131.2 1082.19     135 1081.72   144.6 1081.96   146.2 1082.09   163.9 1083.58
   173.6 1084.16   212.1 1085.86   250.7 1087.41   298.9 1089.74   308.5 1090.48
   318.2 1091.51   327.8 1092.38   347.1 1093.36   356.7 1094.11   366.4 1095.11
   385.7 1097.36   395.3 1098.88     405 1100.84   433.9 1107.27   472.4 1116.67
#Mann= 3 , 0 , 0
       0      .1       0   131.2    .045       0   146.2     .08       0
Bank Sta=131.2,146.2
XS Rating Curve= 0 ,0
Exp/Cntr=0.3,0.1

Type RM Length L Ch R = 1 ,6320.7  ,406.5,416.9,427
XS GIS Cut Line= 2
     1786046.335      313432.274     1786536.036      313369.924
#Sta/Elev= 30
       0 1163.63     9.7 1159.48    38.7 1146.59    67.8 1133.95    77.4 1129.62
    87.1 1124.79    96.8 1119.48   145.2 1092.36   154.9 1087.18   164.6  1083.3
   174.2 1081.14   180.8 1080.38   183.9 1080.02   193.6 1079.69   203.3 1080.61
     2101081.612   222.6 1083.38   290.4 1090.56   309.7 1092.81   319.4 1094.26
   329.1 1096.33   338.8 1098.88   367.8 1106.84   425.9 1122.54   435.6    1125
   445.3 1126.83   454.9 1128.78   464.6 1131.92   474.3 1135.68   493.6  1143.4
#Mann= 3 , 0 , 0
       0      .1       0   180.8    .045       0     210      .1       0
Bank Sta=180.8,210
XS Rating Curve= 0 ,0
Exp/Cntr=0.3,0.1

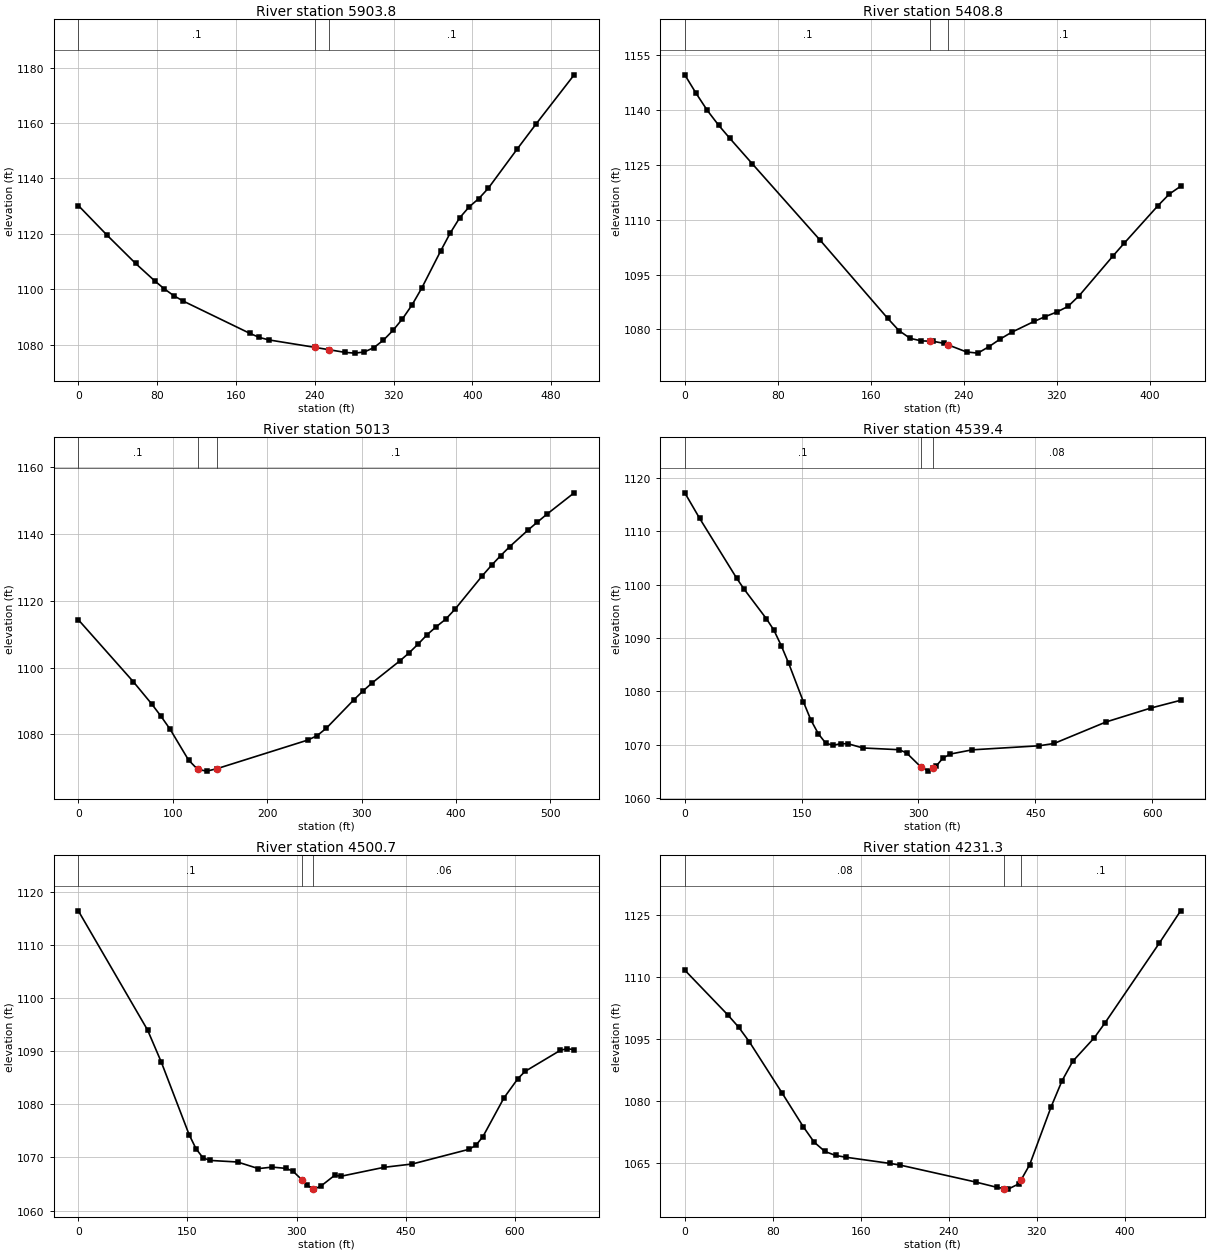
Type RM Length L Ch R = 1 ,5903.8  ,486.5,495,503.4
XS GIS Cut Line= 2
     1786077.962       313731.14     1786554.558      313893.095
#Sta/Elev= 30
       0 1130.23      29 1119.58    58.1 1109.34    77.4 1103.08    87.1  1100.2
    96.8 1097.72   106.5 1095.74   174.2 1084.08   183.9 1082.61   193.6 1081.72
   239.9 1079.06   254.9 1078.17     271 1077.22   280.7 1076.96   290.4 1077.38
   300.1 1078.96   309.8 1081.66   319.4 1085.14   329.1 1089.33   338.8 1094.35
   348.5 1100.32   367.8 1113.78   377.5 1120.25   387.2  1125.8   396.9 1129.78
   406.6 1132.73   416.2 1136.45   445.3 1150.49   464.6 1159.59   503.4 1177.39
#Mann= 3 , 0 , 0
       0      .1       0   239.9    .045       0   254.9      .1       0
Bank Sta=239.9,254.9
XS Rating Curve= 0 ,0
Exp/Cntr=0.3,0.1

Type RM Length L Ch R = 1 ,5408.8  ,402.4,395.8,387.2
XS GIS Cut Line= 2
     1785813.854      314014.408     1786139.845      314289.614
#Sta/Elev= 30
       0 1149.61     9.7 1144.56    19.4 1139.86    29.1 1135.83    38.8 1132.22
    58.2 1125.23   116.4  1104.4   174.5 1083.04   184.2 1079.68   193.9 1077.54
   203.6 1076.85   211.1 1076.77   213.3 1076.75     223 1076.18   226.1 1075.81
   242.4 1073.82   252.1  1073.5   261.8 1075.29   271.5 1077.38   281.2  1079.2
   300.6 1082.18   310.3 1083.51     320 1084.73   329.7 1086.27   339.4 1089.24
   368.4 1100.07   378.1 1103.58   407.2 1113.86   416.9 1117.01   426.6 1119.13
#Mann= 3 , 0 , 0
       0      .1       0   211.1    .045       0   226.1      .1       0
Bank Sta=211.1,226.1
XS Rating Curve= 0 ,0
Exp/Cntr=0.3,0.1

Type RM Length L Ch R = 1 ,5013    ,490.3,473.6,457.1
XS GIS Cut Line= 2
     1785630.235      314430.093     1786121.168      314616.459
#Sta/Elev= 30
       0 1114.27    58.4  1095.7    77.8 1089.07    87.5 1085.45    97.2 1081.55
   116.7 1072.36   126.4 1069.55   136.1 1069.04   146.9 1069.78   243.1 1078.33
   252.8 1079.62   262.6 1081.85   291.7 1090.32   301.5 1092.99   311.2 1095.42
   340.4 1101.96   350.1 1104.32   359.8 1106.99   369.5 1109.84   379.2 1112.22
     389 1114.42   398.7 1117.34   427.9 1127.44   437.6 1130.54   447.3 1133.44
     457 1136.15   476.5 1141.13   486.2 1143.45   495.9 1145.73   525.1 1152.19
#Mann= 3 , 0 , 0
       0      .1       0   126.4    .045       0   146.9      .1       0
Bank Sta=126.4,146.9
XS Rating Curve= 0 ,0
Exp/Cntr=0.3,0.1

Type RM Length L Ch R = 1 ,4539.4  ,35.4,38.7,41.9
XS GIS Cut Line= 4
     1785389.982      314830.016      1785575.13      314964.112
     1785707.447      314917.294     1785914.044      314747.155
#Sta/Elev= 30
       0 1117.18      19 1112.41    66.7 1101.16    76.2 1099.12   104.8 1093.58
   114.3 1091.48   123.8 1088.56   133.4 1085.23   152.4 1077.98   161.9 1074.61
   171.5 1072.03     181 1070.27   190.5 1069.88     200 1070.17   209.6 1070.17
   228.6 1069.38   275.4 1069.05   284.8 1068.44   303.2 1065.81   312.8 1065.04
   318.2 1065.54   322.2 1065.91   331.5 1067.49   340.9 1068.24     369 1069.03
     455 1069.79   474.1 1070.22     541 1074.26   598.4 1076.86   636.6 1078.31
#Mann= 3 , 0 , 0
       0      .1       0   303.2    .045       0   318.2     .08       0
Bank Sta=303.2,318.2
XS Rating Curve= 0 ,0
Exp/Cntr=0.3,0.1

Type RM Length L Ch R = 1 ,4500.7  ,238.7,269.4,299.7
XS GIS Cut Line= 5
      1785378.41      314844.311      1785579.78      314988.155
     1785691.822      314965.905     1785808.141      314877.364
     1785981.752      314870.419
#Sta/Elev= 30
       0 1116.38    95.2 1093.96   114.2 1087.88   152.3 1074.29   161.8 1071.63
   171.3 1069.94   180.8 1069.44   218.9 1069.14   247.5  1067.9   266.5 1068.18
   285.6 1067.94   295.1 1067.41     308 1065.71   314.1 1064.77     323 1064.09
   323.6 1064.04   333.1 1064.57   352.2 1066.62   361.7 1066.48   420.2 1068.14
   459.2 1068.77   536.8 1071.52   546.5 1072.28   556.2 1073.92   585.1  1081.2
   604.4 1084.84   614.1 1086.18   662.3 1090.12     672 1090.47   681.6 1090.24
#Mann= 3 , 0 , 0
       0      .1       0     308    .045       0     323     .06       0
Bank Sta=308,323
XS Rating Curve= 0 ,0
Exp/Cntr=0.3,0.1

Type RM Length L Ch R = 1 ,4231.3  ,368,378.7,389.4
XS GIS Cut Line= 2
     1785336.442      314894.552     1785532.402      315300.597
#Sta/Elev= 26
       0  1111.7    39.2 1100.86      49 1097.91    58.8 1094.34    88.2 1082.12
   107.8 1073.83   117.6 1070.13   127.4 1067.88   137.2  1066.9     147 1066.46
   186.2    1065     196 1064.57   264.6 1060.48   284.2 1059.18   290.7 1058.91
     294 1058.77   303.8 1060.05   305.7 1060.94   313.6 1064.65   333.2 1078.71
     343 1084.93   352.8 1089.67   372.4 1095.36   382.2 1098.98   431.3 1118.15
   450.9 1126.04
#Mann= 3 , 0 , 0
       0     .08       0   290.7    .045       0   305.7      .1       0
Bank Sta=290.7,305.7
XS Rating Curve= 0 ,0
Exp/Cntr=0.3,0.1