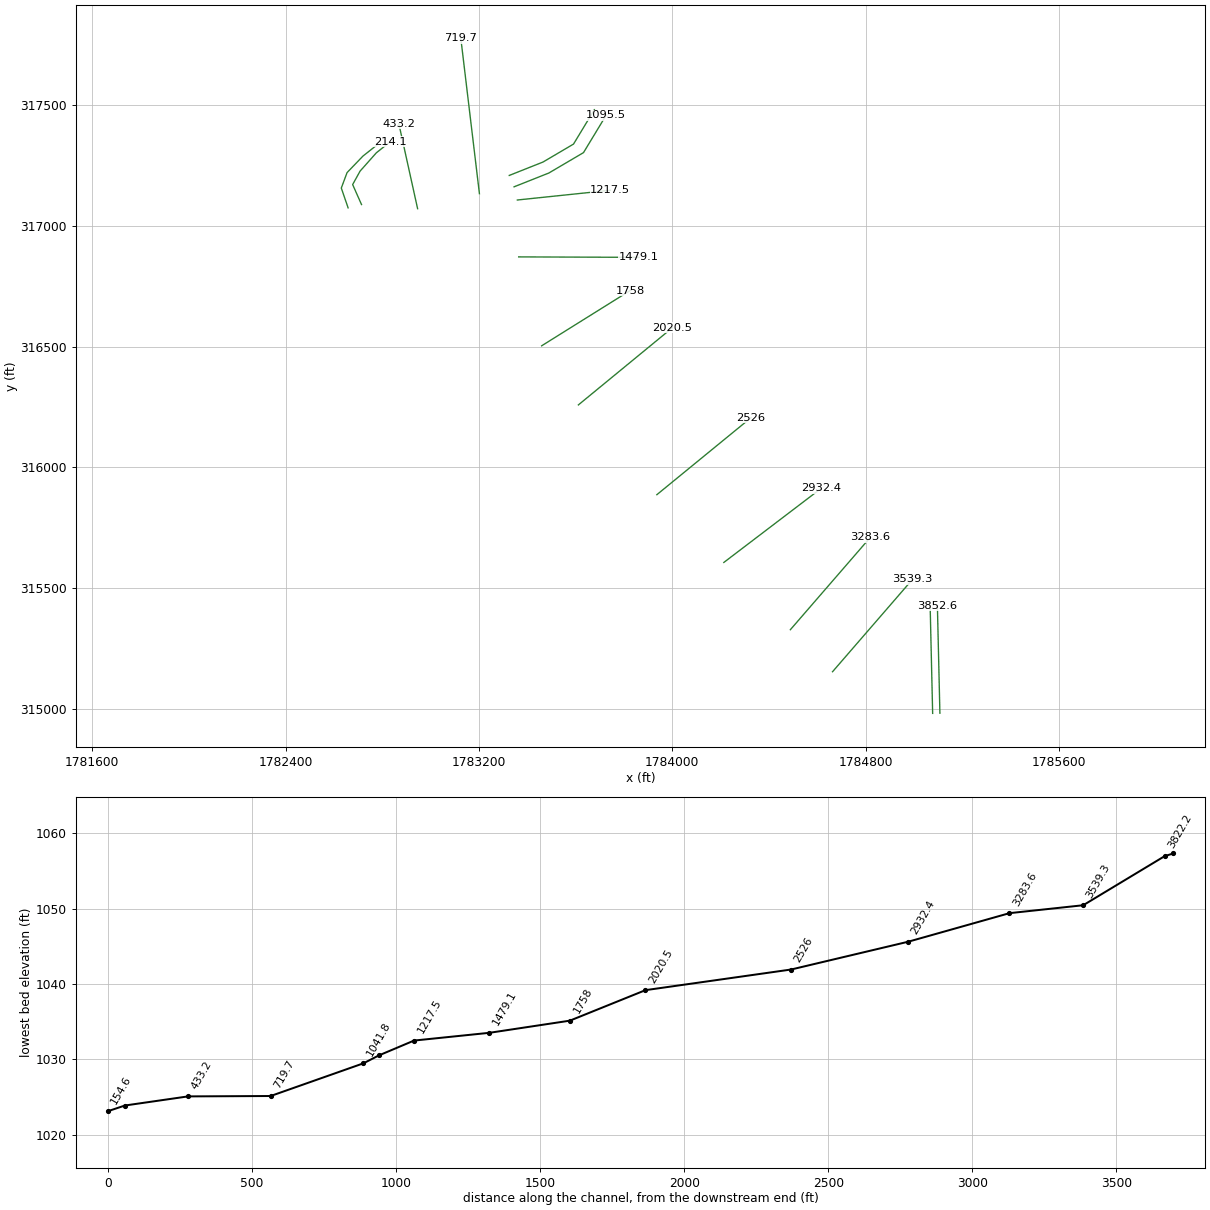
HEC-RAS study PlummerRun.prj: PlummerRun

--- PlummerRun.g01 (geometry) --- (continued)

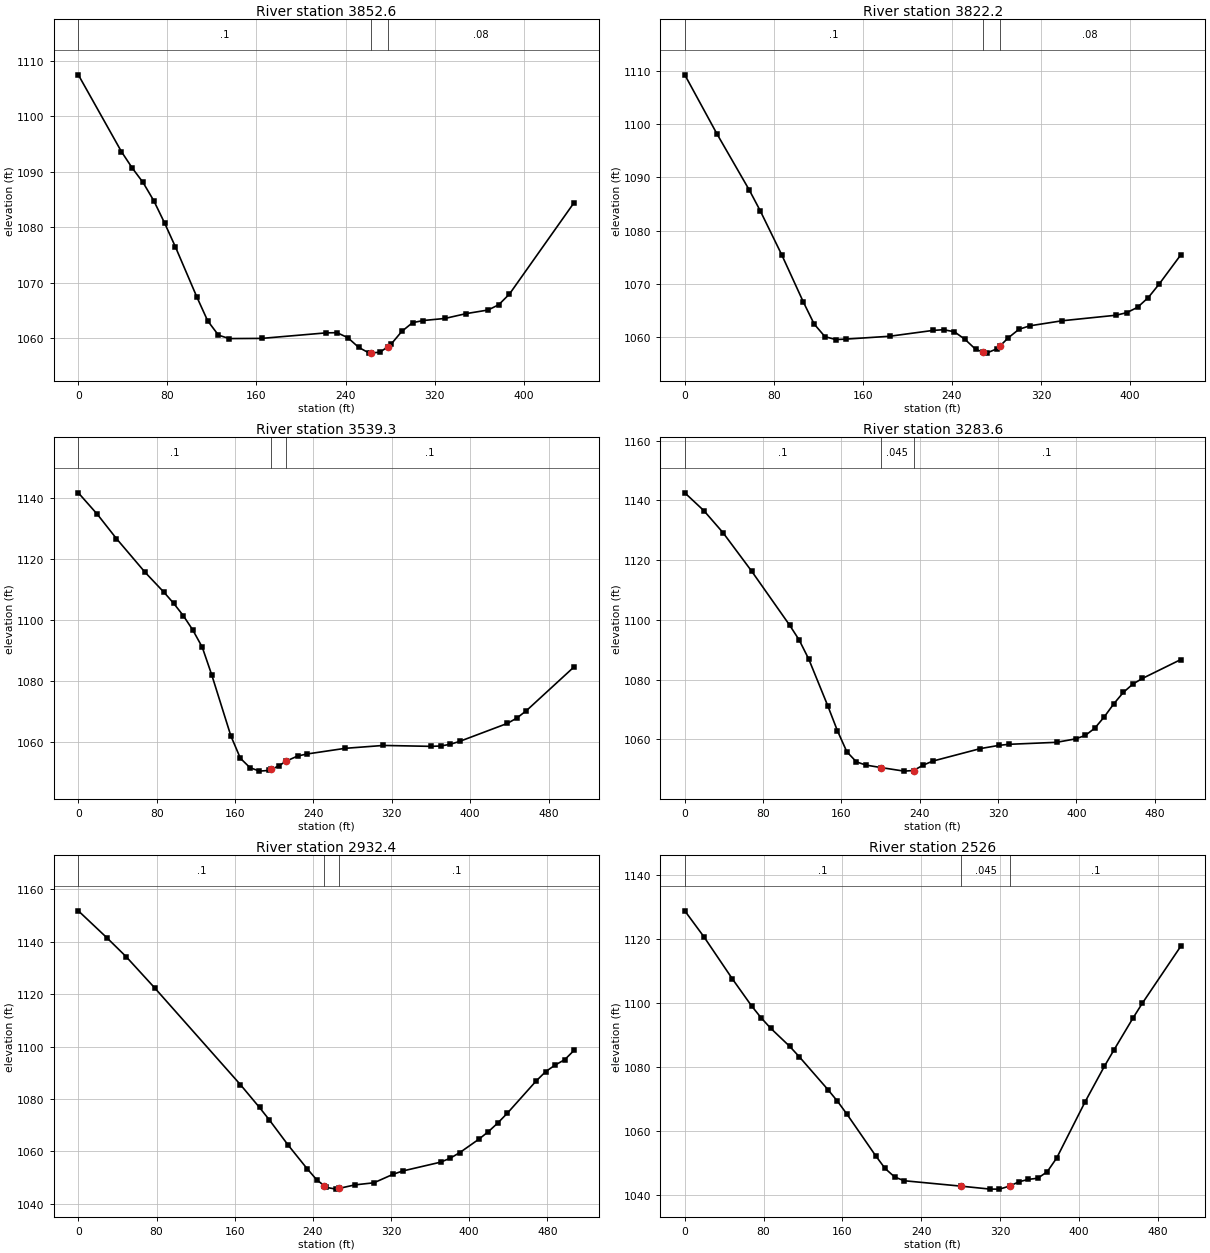
Type RM Length L Ch R = 1 ,3852.6  ,30.4,30.4,30.4
XS GIS Cut Line= 2
     1785107.498      314983.209     1785097.082      315428.521
#Sta/Elev= 30
       0 1107.44    38.7 1093.62    48.4 1090.67    58.1 1088.07    67.8 1084.77
    77.5 1080.76    87.2 1076.47   106.5 1067.43   116.2 1063.15   125.9 1060.57
   135.6 1059.96   164.6 1059.99   222.7 1060.99   232.4 1061.02   242.1 1060.12
   251.8 1058.38   261.4 1057.34   262.9 1057.37   271.1 1057.51   277.9 1058.49
   280.8 1058.91   290.5 1061.24   300.2 1062.82   309.9 1063.21   329.2 1063.58
   348.6 1064.46     368  1065.1   377.6 1066.04   387.3 1067.98   445.4 1084.45
#Mann= 3 , 0 , 0
       0      .1       0   262.9    .045       0   277.9     .08       0
Bank Sta=262.9,277.9
XS Rating Curve= 0 ,0
Exp/Cntr=0.3,0.1

Type RM Length L Ch R = 1 ,3822.2  ,299.5,282.8,266.1
XS GIS Cut Line= 2
     1785077.507      314982.507      1785067.09       315427.82
#Sta/Elev= 30
       0 1109.27      29 1098.13    58.1 1087.56    67.8 1083.71    87.2  1075.4
   106.5 1066.58   116.2 1062.45   125.9 1060.07   135.6 1059.53   145.2 1059.62
     184 1060.15   222.7 1061.24   232.4 1061.38   242.1    1061   251.8 1059.55
   261.4 1057.67   267.8 1057.21   271.1 1056.98   280.8 1057.84   282.8 1058.25
   290.5 1059.84   300.2 1061.46   309.9 1062.11   338.9 1063.06   387.3  1064.1
     397 1064.58   406.7 1065.59   416.4 1067.43   426.1 1069.95   445.4  1075.4
#Mann= 3 , 0 , 0
       0      .1       0   267.8    .045       0   282.8     .08       0
Bank Sta=267.8,282.8
XS Rating Curve= 0 ,0
Exp/Cntr=0.3,0.1

Type RM Length L Ch R = 1 ,3539.3  ,255.8,255.7,255.5
XS GIS Cut Line= 2
     1784663.067      315154.736     1784994.378      315537.294
#Sta/Elev= 30
       0 1141.59    19.5 1134.52    38.9  1126.6    68.1 1115.58    87.6 1108.96
    97.3 1105.41   107.1 1101.39   116.8 1096.69   126.5 1091.03   136.2 1081.95
   155.7 1061.99   165.4 1054.67   175.2  1051.6   184.9 1050.46   194.6 1050.69
   196.9 1051.03   204.4 1052.14   211.9 1053.69   223.8 1055.41   233.6 1056.08
   272.5 1057.93   311.4 1058.87   360.1 1058.57   369.8 1058.69   379.6 1059.24
   389.3 1060.21     438  1066.1   447.7 1067.86   457.4 1070.27   506.1 1084.62
#Mann= 3 , 0 , 0
       0      .1       0   196.9    .045       0   211.9      .1       0
Bank Sta=196.9,211.9
XS Rating Curve= 0 ,0
Exp/Cntr=0.3,0.1

Type RM Length L Ch R = 1 ,3283.6  ,355.8,351.3,346.6
XS GIS Cut Line= 2
      1784488.65      315328.759     1784820.144      315711.528
#Sta/Elev= 30
       0  1142.5    19.5 1136.53      39 1129.18    68.2 1116.33   107.1 1098.22
   116.8 1093.28   126.6 1086.88   146.1  1071.2   155.8 1062.98   165.5 1055.88
   175.3  1052.5     185 1051.43   200.61050.591     224 1049.41   233.6 1049.62
   243.4  1051.4   253.2 1052.76   301.9 1056.95   321.3 1058.05   331.1 1058.38
   379.8 1059.05   399.2  1060.2     409 1061.35   418.7 1063.76   428.5  1067.6
   438.2 1071.95   447.9 1075.75   457.7 1078.55   467.4 1080.42   506.4  1086.7
#Mann= 3 , 0 , 0
       0      .1       0   200.6    .045       0   233.6      .1       0
Bank Sta=200.6,233.6
XS Rating Curve= 0 ,0
Exp/Cntr=0.3,0.1

Type RM Length L Ch R = 1 ,2932.4  ,405.7,406.4,407
XS GIS Cut Line= 2
     1784213.423      315607.114     1784617.222      315914.449
#Sta/Elev= 30
       0 1151.83    29.3 1141.52    48.8 1134.38    78.1 1122.43   165.9 1085.48
   185.4 1076.78   195.2 1072.16   214.7 1062.43   234.2 1053.38     244 1049.17
   251.6 1046.92   253.7  1046.3   263.5 1045.62   266.6 1045.88     283 1047.24
   302.5 1048.04     322 1051.27   331.8 1052.53   370.8 1055.92   380.6 1057.43
   390.4 1059.57   409.9 1064.68   419.6 1067.55   429.4 1070.91   439.1 1074.63
   468.4 1086.85   478.2 1090.45   487.9 1092.96   497.7 1095.01   507.4 1098.61
#Mann= 3 , 0 , 0
       0      .1       0   251.6    .045       0   266.6      .1       0
Bank Sta=251.6,266.6
XS Rating Curve= 0 ,0
Exp/Cntr=0.3,0.1

Type RM Length L Ch R = 1 ,2526    ,505.4,505.5,505.7
XS GIS Cut Line= 2
     1783936.182      315887.505     1784325.821      316206.145
#Sta/Elev= 30
       0 1128.71    19.4 1120.62    48.4 1107.44    67.8 1099.06    77.4 1095.37
    87.1 1092.12   106.5 1086.44   116.2 1083.21   145.2 1072.99   154.9 1069.37
   164.6  1065.3   193.6  1052.4   203.3 1048.37     213 1045.72   222.6 1044.55
   280.51042.856   309.8 1041.94   319.4 1041.93     3301042.909   338.8 1044.17
   348.5 1044.96   358.2 1045.32   367.8 1047.32   377.5 1051.63   406.5 1069.25
   425.9 1080.22   435.6 1085.31   454.9 1095.25   464.6 1099.97   503.3 1117.59
#Mann= 3 , 0 , 0
       0      .1       0   280.5    .045       0     330      .1       0
Bank Sta=280.5,330
XS Rating Curve= 0 ,0
Exp/Cntr=0.3,0.1

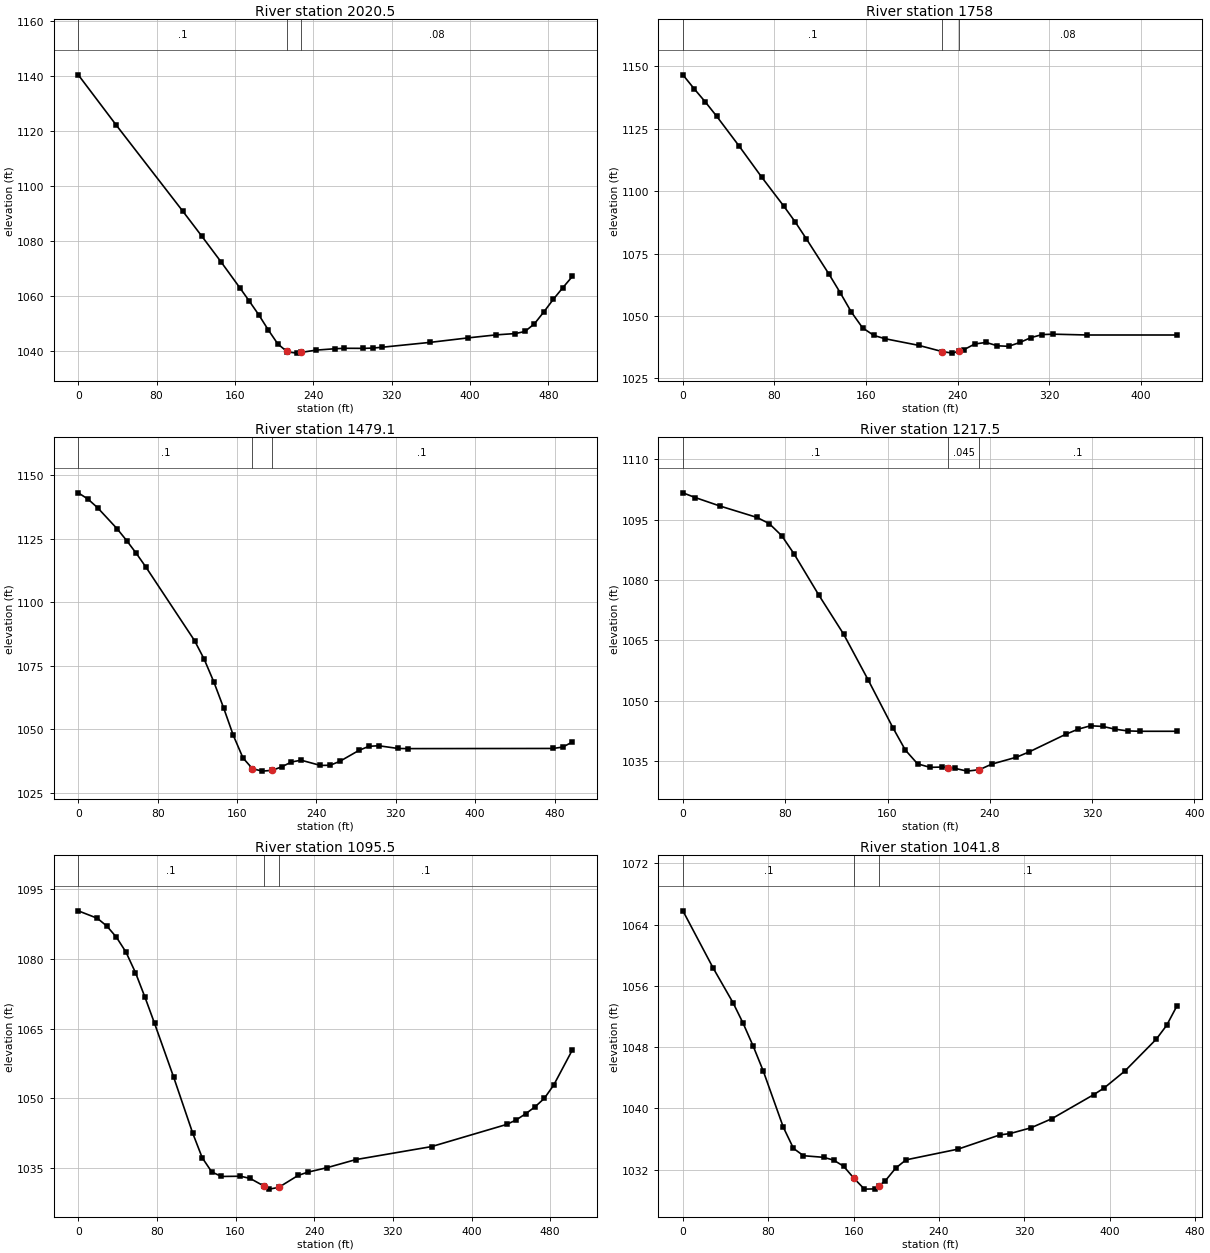
Type RM Length L Ch R = 1 ,2020.5  ,265.4,262.4,259.5
XS GIS Cut Line= 2
     1783611.445      316258.979      1784001.42      316579.259
#Sta/Elev= 30
       0 1140.27    38.8    1122   106.8 1090.72   126.2 1081.65   145.6 1072.43
     165 1062.92   174.7 1058.06   184.4 1053.07   194.1 1047.59   203.8 1042.51
   212.7 1039.89   213.5 1039.65   223.2 1039.19   227.7 1039.46   242.6 1040.27
     262 1040.78   271.7 1040.95   291.1 1040.92   300.8 1041.02   310.6 1041.34
   359.1 1043.09   397.9 1044.72     427 1045.83   446.4  1046.3   456.1 1047.05
   465.8 1049.84   475.5  1054.2   485.2 1058.78   494.9    1063   504.6 1067.07
#Mann= 3 , 0 , 0
       0      .1       0   212.7    .045       0   227.7     .08       0
Bank Sta=212.7,227.7
XS Rating Curve= 0 ,0
Exp/Cntr=0.3,0.1

Type RM Length L Ch R = 1 ,1758    ,291.6,278.9,266.2
XS GIS Cut Line= 2
     1783459.468      316503.589     1783825.693      316732.302
#Sta/Elev= 30
       0  1146.6     9.8 1141.04    19.6 1135.74    29.4 1130.08    49.1 1118.09
    68.7 1105.72    88.3 1093.93    98.1 1087.71   107.9 1080.89   127.6 1066.82
   137.4 1059.39   147.2 1051.59     157 1045.27   166.8 1042.24   176.6 1040.91
   206.1 1038.25   226.6 1035.76   235.5 1035.14   241.6 1035.96   245.3 1036.45
   255.1 1038.82     265 1039.42   274.8 1038.07   284.6 1037.87   294.4 1039.41
   304.2 1041.36     314 1042.57   323.8 1042.73   353.3  1042.4   431.8  1042.4
#Mann= 3 , 0 , 0
       0      .1       0   226.6    .045       0   241.6     .08       0
Bank Sta=226.6,241.6
XS Rating Curve= 0 ,0
Exp/Cntr=0.3,0.1

Type RM Length L Ch R = 1 ,1479.1  ,259,261.6,263.9
XS GIS Cut Line= 2
     1783364.365       316871.54     1783862.315      316869.645
#Sta/Elev= 30
       0 1143.17     9.8  1140.7    19.5  1137.3    39.1 1129.04    48.8 1124.35
    58.6 1119.27    68.4 1113.79   117.2 1084.95   126.9 1077.63   136.7 1068.61
   146.5 1058.44   156.2 1047.68     166 1038.73   175.6 1034.47   185.5 1033.53
   195.3 1033.84     205 1035.21   214.8 1037.12   224.6 1037.84   244.1 1035.77
   253.9 1035.85   263.6 1037.39   283.2 1041.77   292.9  1043.3   302.7 1043.53
   322.2 1042.46     332  1042.4   478.4 1042.46   488.2    1043     498    1045
#Mann= 3 , 0 , 0
       0      .1       0   175.6    .045       0   195.3      .1       0
Bank Sta=175.6,195.3
XS Rating Curve= 0 ,0
Exp/Cntr=0.3,0.1

Type RM Length L Ch R = 1 ,1217.5  ,112.3,122,131.7
XS GIS Cut Line= 2
     1783358.905      317106.967     1783743.198      317147.116
#Sta/Elev= 30
       0 1101.64     9.7 1100.46      29 1098.36      58 1095.52    67.6 1093.97
    77.3 1090.98    86.9 1086.48   106.3 1076.23   125.6 1066.57   144.9 1055.14
   164.2 1043.29   173.9 1037.75   183.5 1034.31   193.2 1033.44   202.8 1033.51
   207.6 1033.36   212.5 1033.21   222.2  1032.5   231.8 1032.85   241.5 1034.24
   260.8 1035.96   270.5 1037.24   299.4 1041.66   309.1 1042.93   318.8 1043.77
   328.4  1043.6   338.1 1042.91   347.8 1042.49   357.4  1042.4   386.4  1042.4
#Mann= 3 , 0 , 0
       0      .1       0   207.6    .045       0   231.8      .1       0
Bank Sta=207.6,231.8
XS Rating Curve= 0 ,0
Exp/Cntr=0.3,0.1

Type RM Length L Ch R = 1 ,1095.5  ,54,53.7,53.4
XS GIS Cut Line= 4
     1783345.244      317161.495     1783489.542      317218.774
     1783632.607      317302.997     1783726.587      317458.122
#Sta/Elev= 30
       0 1090.31    19.4 1088.71    29.1 1087.03    38.8 1084.65    48.5 1081.46
    58.2 1077.04    67.9 1071.73    77.6 1066.14      97  1054.6   116.4 1042.56
   126.1 1037.26   135.8 1034.22   145.6 1033.25     165  1033.3   174.8 1032.83
   188.9 1031.19   194.3 1030.53   203.9 1030.91   223.6 1033.47   233.4 1034.17
   252.9 1035.13   282.2 1036.87   359.4 1039.67   435.8 1044.43   445.4 1045.39
   454.9  1046.7   464.5 1048.19     474 1050.02   483.6 1052.89   502.6 1060.45
#Mann= 3 , 0 , 0
       0      .1       0   188.9    .045       0   203.9      .1       0
Bank Sta=188.9,203.9
XS Rating Curve= 0 ,0
Exp/Cntr=0.3,0.1

Type RM Length L Ch R = 1 ,1041.8  ,295.9,322,348.7
XS GIS Cut Line= 4
     1783325.277      317208.581     1783465.267       317264.15
       1783591.3      317338.346     1783677.441      317480.531
#Sta/Elev= 30
       0 1065.79    28.2 1058.37    47.1 1053.77    56.5  1051.1    65.9 1048.13
    75.3  1044.9    94.1 1037.56   103.6  1034.8     113 1033.84   131.8 1033.63
   141.2 1033.27   150.6 1032.47   160.4 1030.88   170.1 1029.48   179.9 1029.51
   183.9 1029.94   189.6 1030.55   199.4 1032.22   209.1  1033.3   257.9  1034.7
   296.9 1036.55   306.6 1036.73   326.2 1037.48   345.8 1038.67   384.9  1041.8
   394.7 1042.67   414.2 1044.89   443.6 1049.04   453.3 1050.84   463.1 1053.41
#Mann= 3 , 0 , 0
       0      .1       0   160.4    .045       0   183.9      .1       0
Bank Sta=160.4,183.9
XS Rating Curve= 0 ,0
Exp/Cntr=0.3,0.1

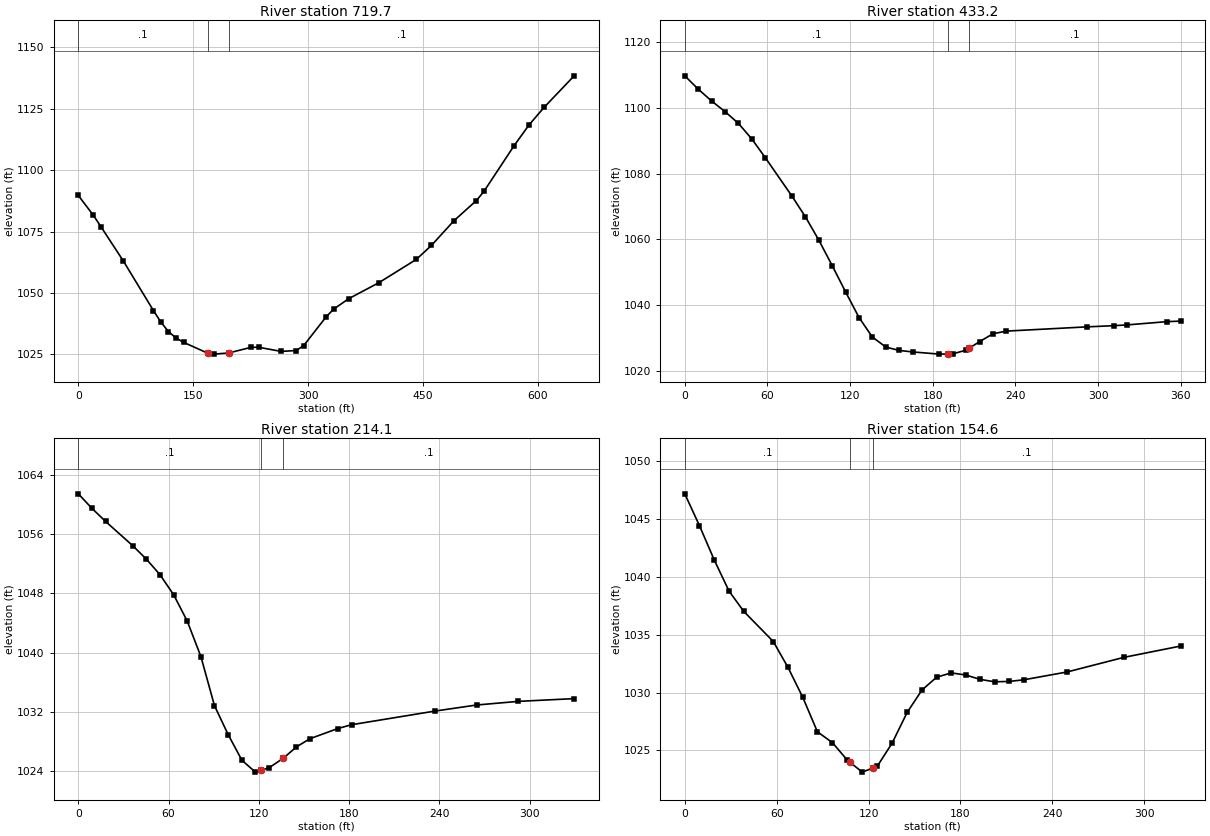
Type RM Length L Ch R = 1 ,719.7   ,283.7,286.5,287.4
XS GIS Cut Line= 2
     1783201.944       317133.01     1783124.949      317775.974
#Sta/Elev= 30
       0  1089.7    19.6 1081.65    29.4 1077.06    58.9 1062.99    98.1 1042.86
   107.9 1038.12   117.7 1034.32   127.6  1031.7   137.4 1029.95     169 1025.52
   176.6 1025.14   196.2  1025.6   225.7 1027.91   235.5 1027.93   264.9 1026.25
   284.5  1026.6   294.3  1028.6   323.8 1040.36   333.6 1043.48   353.2 1047.71
   392.5  1054.2   441.5  1063.7   461.1 1069.35   490.6 1079.43     520 1087.66
   529.8 1091.38   569.1 1109.95   588.7 1118.43   608.3 1125.55   647.6  1138.4
#Mann= 3 , 0 , 0
       0      .1       0     169    .045       0   196.2      .1       0
Bank Sta=169,196.2
XS Rating Curve= 0 ,0
Exp/Cntr=0.3,0.1

Type RM Length L Ch R = 1 ,433.2   ,241.4,219.1,197.8
XS GIS Cut Line= 2
     1782946.086      317071.072     1782868.434      317422.639
#Sta/Elev= 30
       0 1109.83     9.7 1105.79    19.5 1102.15    29.2 1098.94    38.9 1095.36
    48.6 1090.64    58.4 1084.93    77.8  1073.2    87.6 1066.88    97.3 1059.81
     107 1052.06   116.8 1043.99   126.5 1036.24   136.2 1030.28     146 1027.23
   155.7 1026.21   165.4 1025.76   184.9 1025.09   191.2 1025.14   194.6 1025.17
   204.4 1026.33   206.2 1026.81   214.1 1028.92   223.8  1031.3   233.5  1032.1
   291.9 1033.39   311.4 1033.75   321.1 1033.99   350.3 1034.99     360 1035.14
#Mann= 3 , 0 , 0
       0      .1       0   191.2    .045       0   206.2      .1       0
Bank Sta=191.2,206.2
XS Rating Curve= 0 ,0
Exp/Cntr=0.3,0.1

Type RM Length L Ch R = 1 ,214.1   ,53,59.5,64.6
XS GIS Cut Line= 5
     1782713.983      317088.138      1782677.29       317170.91
      1782708.01      317226.376     1782775.422      317302.322
     1782833.448      317348.401
#Sta/Elev= 24
       0  1061.4       9 1059.45    18.1 1057.68    36.2  1054.4    45.3 1052.58
    54.3 1050.49    63.4 1047.78    72.4 1044.24    81.5 1039.44    90.5 1032.84
    99.6 1028.94   108.7 1025.49   117.7 1023.88   121.3 1024.11   126.8 1024.47
   136.3 1025.76   144.9 1027.27   153.9 1028.38   172.4 1029.75   181.6 1030.27
     237 1032.11   264.8 1032.93   292.5 1033.42   329.6 1033.79
#Mann= 3 , 0 , 0
       0      .1       0   121.3    .045       0   136.3      .1       0
Bank Sta=121.3,136.3
XS Rating Curve= 0 ,0
Exp/Cntr=0.3,0.1

Type RM Length L Ch R = 1 ,154.6   ,147.3,154.6,162.4
XS GIS Cut Line= 5
     1782658.517      317074.485     1782630.358      317156.404
     1782654.251      317220.403     1782719.956      317288.668
     1782777.982      317334.748
#Sta/Elev= 28
       0 1047.18     9.6 1044.42    19.2 1041.47    28.9 1038.77    38.5 1037.02
    57.8 1034.41    67.4 1032.17      77  1029.6    86.6 1026.61    96.4 1025.67
   106.1 1024.16   107.7 1023.99   115.9 1023.12   122.7 1023.47   125.7 1023.63
   135.4 1025.63   145.2 1028.28   154.9 1030.22   164.4 1031.32   173.9  1031.7
   183.4 1031.52   192.8 1031.14   202.3 1030.93   211.8 1030.96   221.3  1031.1
   249.7 1031.78   286.7 1033.04   323.8 1034.02
#Mann= 3 , 0 , 0
       0      .1       0   107.7    .045       0   122.7      .1       0
Bank Sta=107.7,122.7
XS Rating Curve= 0 ,0
Exp/Cntr=0.3,0.1

Chan Stop Cuts=-1
Use User Specified Reach Order=0
Composite Channel Slope=5